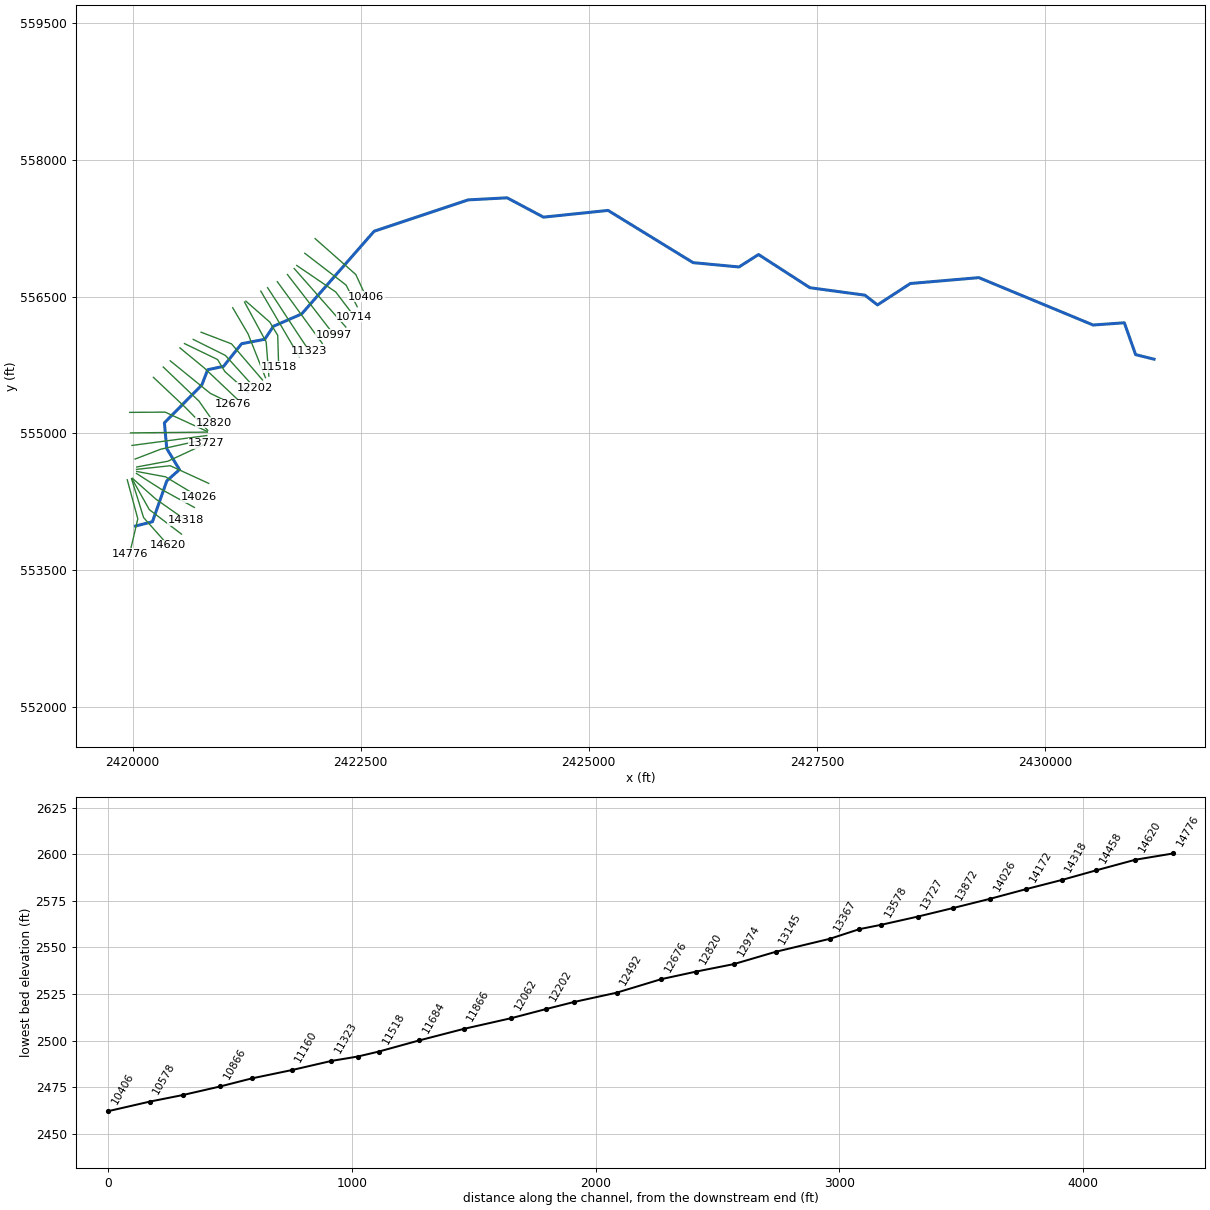
--- LONGRN1.prj (project) ---

Proj Title=LONGRN1
Current Plan=p01
Default Exp/Contr=0,0
English Units
Geom File=g01
Flow File=f01
Plan File=p01
BEGIN DESCRIPTION:
Stream Name: Long Run 1
Flood Zone: Approximate
Pendleton County, West Virginia
HEC-RAS Version: 5.0.7
Hydrology Method:
Regression
Model Notes:
NA
END DESCRIPTION:
DSS File=dss
DSS Export Rating Curves= 0
DSS Export Rating Curve Sorted= 0
DSS Export Volume Flow Curves= 0
DXF OffsetX= 0
DXF OffsetY= 0
DXF ScaleX= 0
DXF ScaleY= 0

--- LONGRN1.p01 (plan) ---

Plan Title=Floodplain
Program Version=5.07
Short Identifier=Floodplain
Geom File=g01
Flow File=f01
Subcritical Flow
K Sum by GR= 0
Std Step Tol= 0.01
Critical Tol= 0.01
Num of Std Step Trials= 20
Max Error Tol= 0.3
Flow Tol Ratio= 0.001
Split Flow NTrial= 30
Split Flow Tol= 0.02
Split Flow Ratio= 0.02
Log Output Level= 0
Friction Slope Method= 1
Unsteady Friction Slope Method= 2
Unsteady Bridges Friction Slope Method= 1
Parabolic Critical Depth
Global Vel Dist= 0 , 0 , 0
Global Log Level= 0
CheckData=False
Encroach Param=-1 ,0,0, 0
Computation Interval=0.1SEC
Output Interval=1MIN
Instantaneous Interval=Max Profile
Mapping Interval=1HOUR
Computation Time Step Use Courant=        0
Computation Time Step Use Time Series=    0
Computation Time Step Count To Double=0
Computation Time Step Max Doubling=0
Computation Time Step Max Halving=0
Computation Time Step Residence Courant=0
Run HTab= 0
Run UNet= 0
Run Sediment= 0
Run PostProcess= 0
Run WQNet= 0
Run RASMapper= 0
UNET Theta= 0
UNET Theta Warmup= 0
UNET ZTol= 0
UNET ZSATol= 0
UNET MxIter= 0
UNET Max Iter WO Improvement= 0
UNET MaxInSteps= 0
UNET DtIC= 0
UNET DtMin= 0
UNET MaxCRTS= 0
UNET WFStab= 0
UNET SFStab= 0
UNET WFX= 1
UNET SFX= 1
UNET 1D Methodology=Finite Difference
UNET DSS MLevel= 1
UNET Pardiso=0
UNET DZMax Abort= 0
UNET Use Existing IB Tables= 0
UNET Froude Reduction=False
UNET Froude Limit= 0
UNET Froude Power= 0
UNET D1 Cores= 0
UNET D2 Coriolis=0
UNET D2 Cores= 0
UNET D2 Theta= 1
UNET D2 Theta Warmup= 1
UNET D2 Z Tol= 0.01
UNET D2 Volume Tol= 0.01
UNET D2 Max Iterations= 20
UNET D2 Equation= 0
UNET D2 RampUpFraction=0.1
UNET D2 TimeSlices= 1
UNET D2 BCVolumeCheck=0
UNET D1D2 MaxIter= 0
UNET D1D2 ZTol=0.01
UNET D1D2 QTol=0.1
UNET D1D2 MinQTol=1
DSS File=dss
Write IC File= 0
Write IC File at Fixed DateTime=0
Write IC File at Sim End=0
Echo Input=False
Echo Parameters=False
Echo Output=False
Write Detailed= 0
HDF Write Warmup=0
HDF Write Time Slices=0
HDF Flush=0
HDF Face Node Velocities=0
HDF Compression= 1
HDF Chunk Size= 1
HDF Spatial Parts= 1
HDF Use Max Rows=0
HDF Fixed Rows= 1
Calibration Method= 0
Calibration Iterations= 20
Calibration Max Change=0.05
Calibration Tolerance=0.2
Calibration Maximum=1.5
Calibration Minimum=0.5
Calibration Optimization Method= 1
WQ AD Non Conservative
WQ ULTIMATE=-1
WQ Max Comp Step=1HOUR
WQ Output Interval=15MIN
WQ Output Selected Increments= 0
WQ Output face flow=0
WQ Output face velocity=0
WQ Output face area=0
WQ Output face dispersion=0
WQ Output cell volume=0
WQ Output cell surface area=0
WQ Output cell continuity=0
WQ Output cumulative cell continuity=0
WQ Output face conc=0
WQ Output face dconc_dx=0
WQ Output face courant=0
WQ Output face peclet=0
WQ Output face adv mass=0
WQ Output face disp mass=0
WQ Output cell mass=0
WQ Output cell source sink temp=0
WQ Output nsm pathways=0
WQ Output nsm derived pathways=0
WQ Output MaxMinRange=-1
WQ Daily Max Min Mean=-1
WQ Daily Range=0
WQ Daily Time=0
WQ Create Restart=0
WQ Fixed Restart=0
WQ System Summary=0
WQ Write To DSS=0
WQ Use Fixed Temperature=0
Sorting and Armoring Iterations= 10
XS Update Threshold= 0.02
Bed Roughness Predictor= 0
Hydraulics Update Threshold= 0.02
Energy Slope Method= 1
Volume Change Method= 1
Sediment Retention Method= 0
XS Weighting Method= 0
Number of US Weighted Cross Sections= 1
Number of DS Weighted Cross Sections= 1
Upstream XS Weight=0
Main XS Weight=1
Downstream XS Weight=0
Number of DS XS's Weighted with US Boundary= 1
Upstream Boundary Weight= 1
Weight of XSs Associated with US Boundary= 0
Number of US XS's Weighted with DS Boundary= 1
Downstream Boundary Weight= 0.5
Weight of XSs Associated with DS Boundary= 0.5
Percentile Method= 0
Sediment Output Level= 3
Mass or Volume Output= 0
Output Increment Type= 1
Profile and TS Output Increment= 1
XS Output Flag= 0
XS Output Increment= 10
Write Gradation File= 0
Read Gradation Hotstart= 0
Write HDF5 File= 1
Write Binary Output= 1
Write DSS Sediment File= 0
SV Curve= 0
Specific Gage Flag= 0

--- LONGRN1.f01 (steady flow) ---

Flow Title=Flows
Program Version=5.07
Number of Profiles= 6
Profile Names=P100yr,P10yr,P25yr,P50yr,P500yr,P101yr
River Rch & RM=LONGRN1,Main            ,14776
     572     267     378     472     838     696
River Rch & RM=LONGRN1,Main            ,12492
     665     310     439     549     976     809
River Rch & RM=LONGRN1,Main            ,10997
     772     360     509     637    1135     939
River Rch & RM=LONGRN1,Main            ,8404
    1036     480     681     853    1527    1260
River Rch & RM=LONGRN1,Main            ,4626
    1156     535     760     952    1707    1407
Boundary for River Rch & Prof#=LONGRN1,Main            , 1
Up Type= 0
Dn Type= 3
Dn Slope=0.01788
Boundary for River Rch & Prof#=LONGRN1,Main            , 2
Up Type= 0
Dn Type= 3
Dn Slope=0.01788
Boundary for River Rch & Prof#=LONGRN1,Main            , 3
Up Type= 0
Dn Type= 3
Dn Slope=0.01788
Boundary for River Rch & Prof#=LONGRN1,Main            , 4
Up Type= 0
Dn Type= 3
Dn Slope=0.01788
Boundary for River Rch & Prof#=LONGRN1,Main            , 5
Up Type= 0
Dn Type= 3
Dn Slope=0.01788
Boundary for River Rch & Prof#=LONGRN1,Main            , 6
Up Type= 0
Dn Type= 3
Dn Slope=0.01788
DSS Import GetInterval= 0
DSS Import GetPeak= 0
DSS Import FillOption= 0

--- LONGRN1.g01 (geometry) ---

Geom Title=Geometry
Program Version=5.07

River Reach=LONGRN1         ,Main
Reach XY= 30
2420031.98500004553983.337000012     2420217.472554030.657000005
2420374.90100002554478.6009999962420513.63500002554602.686000004
     2420374.463554832.731999993     2420348.792555115.810000002
2420759.01200002555531.0559999942420823.14600003555698.216000021
     2420996.854555734.8900000162421194.50100002555983.206000015
2421448.59599999556031.8390000022421542.61500004556174.070000008
     2421853.516556310.1050000192422647.72999999557217.179000005
2423677.70300001      557560.9122424105.23000002557583.653999999
2424503.32600003557371.5630000082425211.47700003557445.311000004
2426143.20900002556872.4800000042426646.13600004556825.093999997
2426860.49100003556961.4960000072427423.74900001556597.528999999
2428026.53299999556515.8830000162428164.14600003556408.943000004
2428524.46100003556643.6589999942429275.20700002556708.137999997
     2430527.616556188.5269999952430869.82800001      556212.809
2430993.47000003555863.7389999932431195.82231012555813.788434058

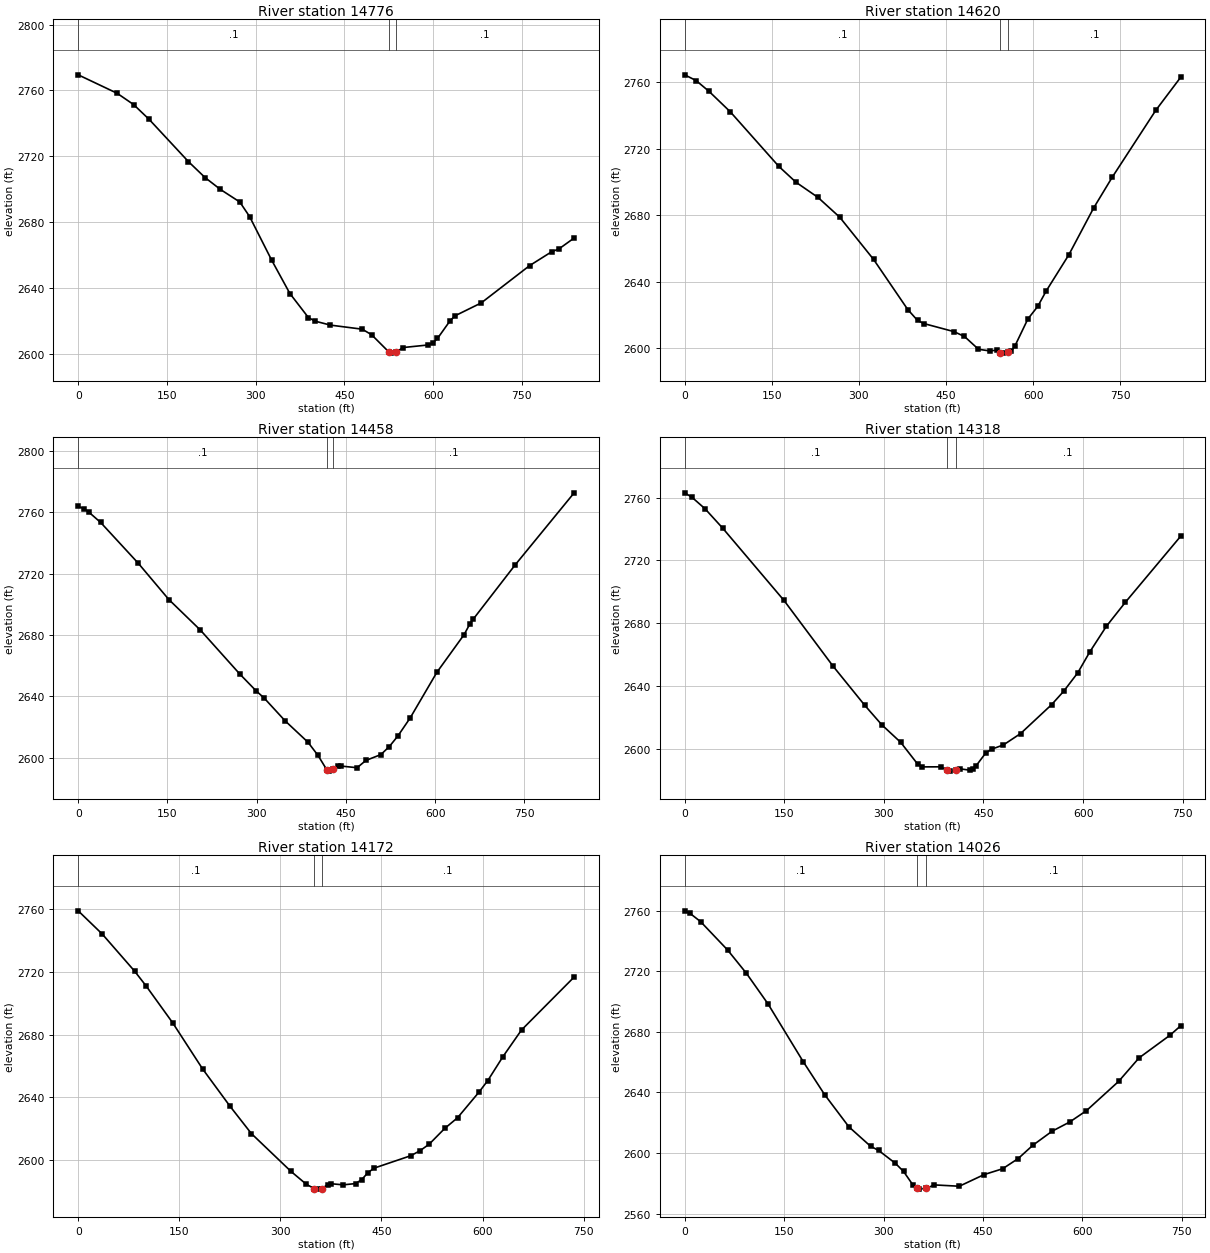
Type RM Length L Ch R = 1 ,14776   ,156.1,156.1,156.1
XS GIS Cut Line= 3
2419941.59270592 554490.582751372420057.25506732554062.772712471
     2419967.254      553677.984
#Sta/Elev= 30
       0 2769.45    65.9 2758.22    93.7 2751.37   119.8 2742.43   186.1 2716.82
   214.3  2707.1   240.4 2699.85   273.1 2692.24   289.7 2683.38   326.9 2656.98
   357.8 2636.66   389.1 2622.06   400.2  2619.9   426.3 2617.47     480    2615
   495.9 2611.64   525.1 2601.16   529.2 2600.46   537.4 2601.23   549.7 2603.87
   590.8 2605.39     599 2606.56   607.3 2609.37   627.8 2619.71   636.4 2623.03
   681.2 2630.94   762.9 2653.57   800.3 2662.02   812.6 2663.74   838.3 2670.37
#Mann= 3 ,-1 , 0
       0      .1       0   525.1    .045       0   537.4      .1       0
Bank Sta=525.1,537.4
XS Rating Curve= 0 ,0
Exp/Cntr=0.3,0.1

Type RM Length L Ch R = 1 ,14620   ,161.5,162.1,167.7
XS GIS Cut Line= 3
2419988.32098392554501.8619908882420120.75815518554076.330932801
     2420391.968      553771.004
#Sta/Elev= 30
       0 2764.36    19.8 2760.89    42.1 2754.37    78.5 2742.15   162.2  2709.3
   191.6 2699.82   229.6 2690.66     267 2678.78   325.4 2653.36   384.2 2623.27
     401 2616.75   411.6 2614.87   463.7    2610   481.9 2607.07     506 2599.38
     526 2598.37   537.3 2598.93     543 2597.42   548.1 2597.07   557.1 2597.46
   562.8 2598.54   568.5  2601.2   591.1 2617.64     608 2625.12   622.3 2634.26
   661.5 2656.12   704.2 2684.25   736.3  2702.8   811.2 2742.97   854.1 2762.84
#Mann= 3 ,-1 , 0
       0      .1       0     543    .045       0   557.1      .1       0
Bank Sta=543,557.1
XS Rating Curve= 0 ,0
Exp/Cntr=0.3,0.1

Type RM Length L Ch R = 1 ,14458   ,139,139.9,140.6
XS GIS Cut Line= 3
2419992.25872757554503.7287050282420183.27476065554163.511859022
2420535.99378524 553895.00648632
#Sta/Elev= 30
       0 2763.71    10.1 2762.09    17.5 2760.07    37.6 2753.28   100.9 2726.69
   152.3 2703.06   205.4 2683.13   271.5 2654.56   299.1 2643.55   312.4 2638.95
   347.6 2624.11   386.2 2610.12   403.1  2601.5   417.5 2592.34   422.2 2591.32
   428.7 2592.52   437.3 2594.35   442.4 2594.59   468.7 2593.54   483.5 2598.28
   508.7  2602.1   522.8 2607.29   537.2 2614.18     558 2626.01   602.8 2655.67
   648.6 2680.24   658.5 2687.35   663.5 2690.08   734.4 2725.62   833.5 2772.53
#Mann= 3 ,-1 , 0
       0      .1       0   417.5    .045       0   428.7      .1       0
Bank Sta=417.5,428.7
XS Rating Curve= 0 ,0
Exp/Cntr=0.3,0.1

Type RM Length L Ch R = 1 ,14318   ,145.7,146.6,146.9
XS GIS Cut Line= 3
2419997.85886999554507.1882089212420254.58698961554279.321263941
     2420584.708      554047.119
#Sta/Elev= 30
       0 2762.99    10.8 2760.22    30.7 2752.85    57.4 2740.47   149.6 2694.61
   223.3 2652.96   271.3 2627.96   296.9  2615.6   325.3 2604.49   350.8 2590.69
   357.8 2588.88   385.3 2588.93   394.9 2586.94   399.7 2586.19   408.3 2586.86
   414.4 2587.67   429.1 2586.82     434 2587.77   438.9 2589.59   453.5 2597.77
   462.1  2600.1     480 2602.83   505.9 2610.06   552.5 2628.38   570.9 2636.99
     592 2648.65     610 2661.85     635 2678.16   663.8 2693.52   746.9 2735.37
#Mann= 3 ,-1 , 0
       0      .1       0   394.9    .045       0   408.3      .1       0
Bank Sta=394.9,408.3
XS Rating Curve= 0 ,0
Exp/Cntr=0.3,0.1

Type RM Length L Ch R = 1 ,14172   ,146,146.1,145.9
XS GIS Cut Line= 3
2420042.82991608554559.9787280532420312.83807759554387.455366124
2420677.22657049554187.807750261
#Sta/Elev= 30
       0 2759.06    35.6 2744.25    83.7 2720.51   100.7  2711.1     140 2687.63
   184.6 2658.04   225.4 2634.14     257 2616.74   315.6 2592.64   338.6 2584.33
   350.2 2581.65   356.8 2581.27   361.4 2581.67   370.5 2584.19   375.1 2584.72
   393.3 2584.01   411.6 2584.82   420.7 2587.38   429.8 2591.73   438.9 2594.66
   493.7 2602.65   507.3 2605.85   520.8 2609.98   543.8 2620.02   562.9 2626.88
   594.8  2643.3   607.7 2650.59   630.1 2665.83   657.8 2682.94   735.9 2716.76
#Mann= 3 ,-1 , 0
       0      .1       0   350.2    .045       0   361.4      .1       0
Bank Sta=350.2,361.4
XS Rating Curve= 0 ,0
Exp/Cntr=0.3,0.1

Type RM Length L Ch R = 1 ,14026   ,154.1,154.1,154.6
XS GIS Cut Line= 3
2420045.17922054 554582.29712042 2420361.9775459554523.093961205
     2420726.434      554302.518
#Sta/Elev= 30
       0 2759.85     7.8 2758.25      24 2752.73    64.7 2734.02    93.2 2718.58
   125.8 2698.36   178.7 2660.38   211.2 2638.49   247.8 2617.24   280.4 2604.46
   292.6 2601.69     318 2593.13   330.3 2587.77   344.8 2578.62   349.92576.559
   353.6 2576.13   364.82576.754   376.9 2578.91   414.4 2578.04   451.8 2585.73
   479.8 2589.59   503.2 2596.31   525.4 2605.11   554.3 2614.34   580.7 2620.38
   606.1 2627.89   654.7 2647.22   685.6 2662.77     732 2677.64   748.3 2683.91
#Mann= 3 ,-1 , 0
       0      .1       0   349.9    .045       0   364.8      .1       0
Bank Sta=349.9,364.8
XS Rating Curve= 0 ,0
Exp/Cntr=0.3,0.1

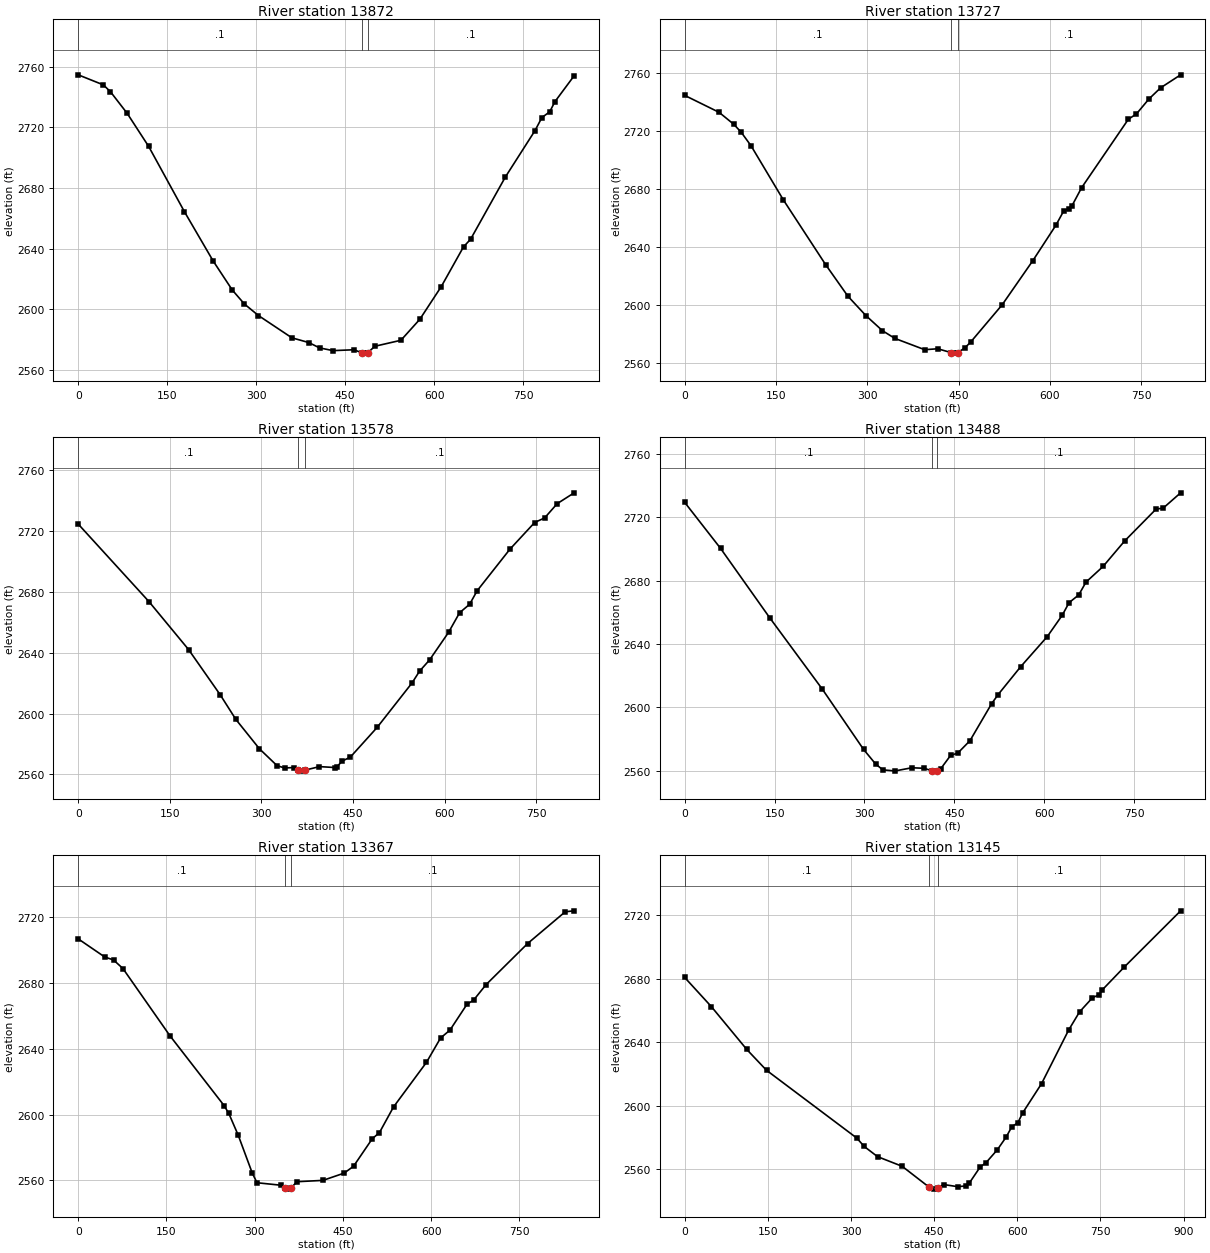
Type RM Length L Ch R = 1 ,13872   ,136.1,144.2,153.6
XS GIS Cut Line= 3
2420042.69939917554605.1375804452420411.93282785554645.071415309
     2420834.154      554451.458
#Sta/Elev= 30
       0  2754.7    42.4 2748.07    54.4 2743.52    82.6 2729.25   118.8 2707.43
   179.1 2664.35   227.4 2631.92   259.6 2612.78     280 2603.54   303.8 2595.89
   360.2 2581.19   388.7 2578.07   406.8 2574.55   429.5 2572.75   464.7 2573.32
   477.9 2571.36   482.2  2571.1   488.3 2571.42   499.9 2575.62   543.9 2579.58
   575.8 2593.43     612 2615.05   649.5 2641.27   661.3  2646.2   719.9 2687.25
     770 2717.96   781.5  2726.5   794.7 2730.33   803.5    2737   835.9 2754.09
#Mann= 3 ,-1 , 0
       0      .1       0   477.9    .045       0   488.3      .1       0
Bank Sta=477.9,488.3
XS Rating Curve= 0 ,0
Exp/Cntr=0.3,0.1

Type RM Length L Ch R = 1 ,13727   ,152.2,149.6,147.4
XS GIS Cut Line= 3
2420045.30973746554631.2409633312420387.59836358554694.883361857
     2420810.568       554891.47
#Sta/Elev= 30
       0 2744.52    56.5 2732.82    80.9 2724.46    93.1 2718.92   109.1 2709.65
   162.2 2672.25   231.4  2627.7     268 2605.88   297.7 2592.42   324.9    2582
   345.3 2576.68   394.2 2568.89   415.6 2569.53   437.7 2566.89   442.4 2566.52
   448.4 2566.95   459.7 2569.94   469.5 2574.04   521.5 2599.91   571.9 2630.42
   609.7 2654.81   622.9 2664.96   631.7  2666.3   636.1 2668.25   651.9 2680.71
   728.8 2728.06     742  2731.7   762.5 2742.01   781.7 2749.73   814.6 2758.71
#Mann= 3 ,-1 , 0
       0      .1       0   437.7    .045       0   448.4      .1       0
Bank Sta=437.7,448.4
XS Rating Curve= 0 ,0
Exp/Cntr=0.3,0.1

Type RM Length L Ch R = 1 ,13578   ,91.9,89.6,88.6
XS GIS Cut Line= 3
2420027.87750181554718.1817938792420306.98688282554825.785160826
     2420807.853      554937.466
#Sta/Elev= 30
       0  2724.6   115.8 2673.65   180.7 2642.11   232.5 2612.38   258.2 2596.14
   296.8 2576.82   325.6 2565.76   337.9  2564.2   354.2 2564.51   360.62562.735
   366.5 2562.13   371.9 2562.82   395.2  2565.1   419.8 2564.51   423.9    2565
   432.1 2568.69   445.7 2571.34   489.5 2590.83   546.8 2620.14   559.1 2627.88
   575.5 2635.26   606.5 2653.33   624.7 2666.31   641.1 2671.85   653.4 2680.74
     707 2708.03   747.6 2725.63     764 2728.66   784.5 2738.02   812.3 2745.15
#Mann= 3 ,-1 , 0
       0      .1       0   360.6    .045       0   371.9      .1       0
Bank Sta=360.6,371.9
XS Rating Curve= 0 ,0
Exp/Cntr=0.3,0.1

Type RM Length L Ch R = 1 ,13488   ,123.5,120.7,120.9
XS GIS Cut Line= 2
2419992.91762473 554867.69097589     2420813.254      554976.056
#Sta/Elev= 30
       0 2729.42    59.8  2700.4   141.7 2656.68   229.9  2611.4   298.5 2573.49
   318.6 2564.28   330.7 2560.58   350.9  2559.9   379.1 2561.92   399.3 2561.58
   412.6 2560.05   419.2 2559.79   421.5 2560.02   427.5 2561.42   443.7  2569.7
   455.8 2571.21     476 2578.99   512.1 2602.32     523 2608.11   560.7 2625.73
     605  2644.7     630 2658.19   641.4 2666.12   657.5    2671   669.6 2679.07
   698.1 2688.96   734.1 2705.05   786.4 2725.11   798.7 2725.87   827.5 2735.43
#Mann= 3 ,-1 , 0
       0      .1       0   412.6    .045       0   421.5      .1       0
Bank Sta=412.6,421.5
XS Rating Curve= 0 ,0
Exp/Cntr=0.3,0.1

Type RM Length L Ch R = 1 ,13367   ,226.6,221.9,218.3
XS GIS Cut Line= 2
2419976.82047046555005.296483323     2420819.911      555013.766
#Sta/Elev= 30
       0 2706.89    45.1 2695.86      60 2694.06      76 2688.85     156  2647.9
     248 2605.45     256 2600.67     272 2587.44     296 2564.28     304  2558.5
     344 2557.02     352 2555.19     360 2554.62  361.22 2555.17     372 2559.14
     416 2559.94     452 2564.35     468 2568.51     500 2585.33     512 2588.95
     536  2604.6     592 2631.74     616 2646.57     632 2651.38     661 2667.15
     672 2669.56   693.3 2679.02     764 2704.05     828 2723.39   843.1 2723.95
#Mann= 3 ,-1 , 0
       0      .1       0     352    .045       0  361.22      .1       0
Bank Sta=352,361.22
XS Rating Curve= 0 ,0
Exp/Cntr=0.3,0.1

Type RM Length L Ch R = 1 ,13145   ,176,171.9,167.8
XS GIS Cut Line= 3
2419968.84915066555230.1266191142420357.47686621 555232.93818401
2420817.15629369555021.573278826
#Sta/Elev= 30
       0 2680.74      48 2662.45     112 2635.47   147.6 2622.38   310.4 2579.77
   323.9 2574.46   347.9 2568.07   392.3 2562.01   441.52548.724     450 2547.65
   456.62548.497   467.1 2550.55   492.2  2549.2   506.7 2549.63   513.3 2551.39
   533.1 2561.61   543.5 2564.24     564 2572.41   579.7  2580.3   590.4 2587.01
   600.8 2589.27   609.8 2595.65   643.8    2614   692.6 2647.66   712.3 2659.09
   735.6 2667.99   747.9 2669.91   753.2 2672.89   792.9 2687.27   894.6 2722.63
#Mann= 3 ,-1 , 0
       0      .1       0   441.5    .045       0   456.6      .1       0
Bank Sta=441.5,456.6
XS Rating Curve= 0 ,0
Exp/Cntr=0.3,0.1

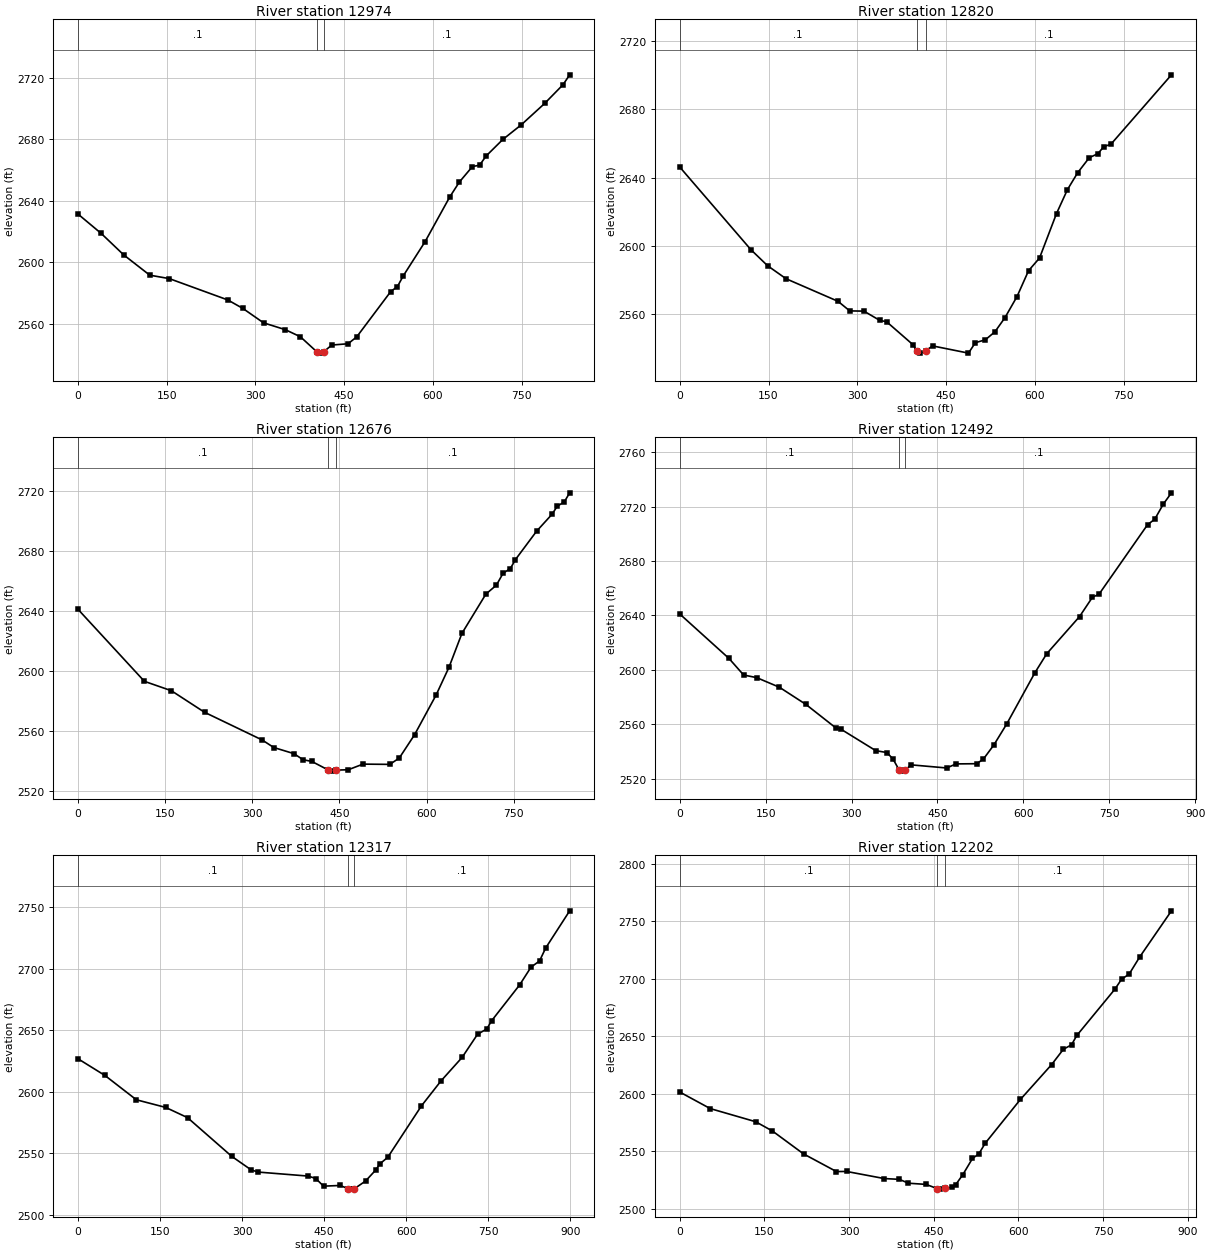
Type RM Length L Ch R = 1 ,12974   ,153.8,153.8,153.6
XS GIS Cut Line= 3
     2420228.499      555614.0622420580.20910406555282.601234229
2420823.79092567555034.043403373
#Sta/Elev= 30
       0 2631.33    39.3 2618.73    77.3 2604.82   121.3 2591.66   154.3 2589.43
   253.2 2575.58   278.8 2570.05   313.7 2560.71   350.5 2556.27     376 2551.67
   404.3 2541.71   409.9 2541.04   415.12541.833   429.1 2546.29   456.6 2547.12
   471.3 2551.62   528.8 2581.04   540.1 2584.28   550.1 2591.31   586.9 2613.46
   628.5 2642.42   644.7 2652.09   666.9  2662.2   678.9 2663.04   690.1 2669.07
   718.2 2679.75   749.4 2689.27     789 2703.17   820.1 2715.36   831.3 2721.74
#Mann= 3 ,-1 , 0
       0      .1       0   404.3    .045       0   415.1      .1       0
Bank Sta=404.3,415.1
XS Rating Curve= 0 ,0
Exp/Cntr=0.3,0.1

Type RM Length L Ch R = 1 ,12820   ,143.8,144.1,144.9
XS GIS Cut Line= 3
     2420335.792      555727.7112420728.59802411  555352.4951599
     2420893.539      555117.198
#Sta/Elev= 30
       0 2646.15   120.2 2597.69   148.4 2588.28   179.6 2580.65   267.3 2567.43
   287.1 2561.81   311.1 2561.67     338 2556.21   349.3 2555.48   394.6 2541.78
   400.12538.455   406.6 2537.14   415.12538.477   427.3 2541.26   487.7 2537.04
   499.3 2543.16   516.2 2544.86   532.4 2549.56   549.4 2557.88   569.7 2570.22
   589.2  2585.4   607.7  2592.8   636.4 2618.89   654.9 2632.94   672.2 2642.86
   691.8 2651.67   706.4 2654.01   716.2 2658.12   728.3 2659.53   830.6 2700.25
#Mann= 3 ,-1 , 0
       0      .1       0   400.1    .045       0   415.1      .1       0
Bank Sta=400.1,415.1
XS Rating Curve= 0 ,0
Exp/Cntr=0.3,0.1

Type RM Length L Ch R = 1 ,12676   ,183.5,183.4,182.5
XS GIS Cut Line= 3
     2420412.025      555796.1392420852.65602411555438.266005622
2421103.99759663555317.663457214
#Sta/Elev= 30
       0 2640.96   114.3 2592.89   160.7 2586.63   217.8 2572.24   317.1 2553.73
     337 2548.72   371.9  2544.6   387.4 2540.56   402.4 2539.44   430.8 2533.71
   436.5 2532.95   443.52533.619   465.2 2533.87   490.6 2537.63   536.8 2537.45
   553.1 2541.71   579.3 2557.19   616.5 2583.78   638.7 2602.34   660.9 2624.89
   702.2 2651.15   720.2 2657.06   731.9 2665.14   744.1 2668.07   753.1  2674.2
   789.5 2693.13   816.2 2704.49     825 2709.79   837.1 2712.67   846.4 2718.72
#Mann= 3 ,-1 , 0
       0      .1       0   430.8    .045       0   443.5      .1       0
Bank Sta=430.8,443.5
XS Rating Curve= 0 ,0
Exp/Cntr=0.3,0.1

Type RM Length L Ch R = 1 ,12492   ,177.4,175.7,172.1
XS GIS Cut Line= 3
2420518.71948695555937.6357006872420782.98046284555720.011611493
2421157.91224347555365.155721174
#Sta/Elev= 30
       0 2641.06    85.9 2608.43   111.5 2596.25   134.2 2594.35     174 2587.27
   220.3 2574.65   272.1 2557.53   281.9 2556.35   342.3 2540.69   361.6 2539.33
   372.3  2534.6   383.3 2526.34   386.9 2525.67   394.12526.537   403.8 2530.28
   466.1 2527.98   482.4 2530.97   518.6 2531.12   530.3 2534.59   548.5  2544.9
   570.8 2560.21   620.1 2597.91   640.8 2611.88   698.1 2639.18   720.7 2653.43
     732 2655.53   816.9 2706.67   829.4 2710.65   844.5 2721.85   858.6 2730.05
#Mann= 3 ,-1 , 0
       0      .1       0   383.3    .045       0   394.1      .1       0
Bank Sta=383.3,394.1
XS Rating Curve= 0 ,0
Exp/Cntr=0.3,0.1

Type RM Length L Ch R = 1 ,12317   ,112.2,114.1,116
XS GIS Cut Line= 4
2420568.38565809555984.9272695822420931.51958643555809.808700618
2421011.22116352555678.0924182392421265.31405384555449.598670956
#Sta/Elev= 30
       0 2626.65    49.3 2613.05   106.7 2593.29   160.3 2587.08   200.2 2578.78
   281.2 2547.24   316.4 2536.34     329 2534.53   420.8 2531.26   434.7 2529.28
   448.8 2523.07     479 2523.62   493.6  2521.1   500.2 2520.65   505.42521.042
   525.6 2527.22   544.5 2536.29   551.8  2541.2   566.2 2546.49   627.8 2588.34
   663.7  2608.7   702.1 2627.71   730.4 2646.58   747.4 2650.91   755.9 2657.43
   807.3 2686.67   828.1 2701.12   843.7 2706.18     855 2716.75   898.8 2746.93
#Mann= 3 ,-1 , 0
       0      .1       0   493.6    .045       0   505.4      .1       0
Bank Sta=493.6,505.4
XS Rating Curve= 0 ,0
Exp/Cntr=0.3,0.1

Type RM Length L Ch R = 1 ,12202   ,141.8,140.9,140.5
XS GIS Cut Line= 3
2420664.45360787556030.6291450352421017.04310968 555855.17528807
     2421337.186       555501.31
#Sta/Elev= 30
       0 2601.39    53.9    2587   134.4 2575.56   164.2 2567.45   219.2 2547.55
   277.5 2532.16   295.4 2532.26   362.2 2526.07     389 2525.38   405.1 2522.02
   436.3 2520.99   456.2 2517.32   461.8 2516.87   469.1 2517.49   481.7 2518.29
   488.7 2520.67   501.5 2529.55   518.5 2543.56   529.8 2547.59   541.1 2556.85
   603.4 2594.94   658.6 2625.22   679.5  2638.6     694 2642.54   703.3 2650.63
   770.5 2690.76   782.7 2699.64     796 2704.05     815 2719.17     871 2759.16
#Mann= 3 ,-1 , 0
       0      .1       0   456.2    .045       0   469.1      .1       0
Bank Sta=456.2,469.1
XS Rating Curve= 0 ,0
Exp/Cntr=0.3,0.1

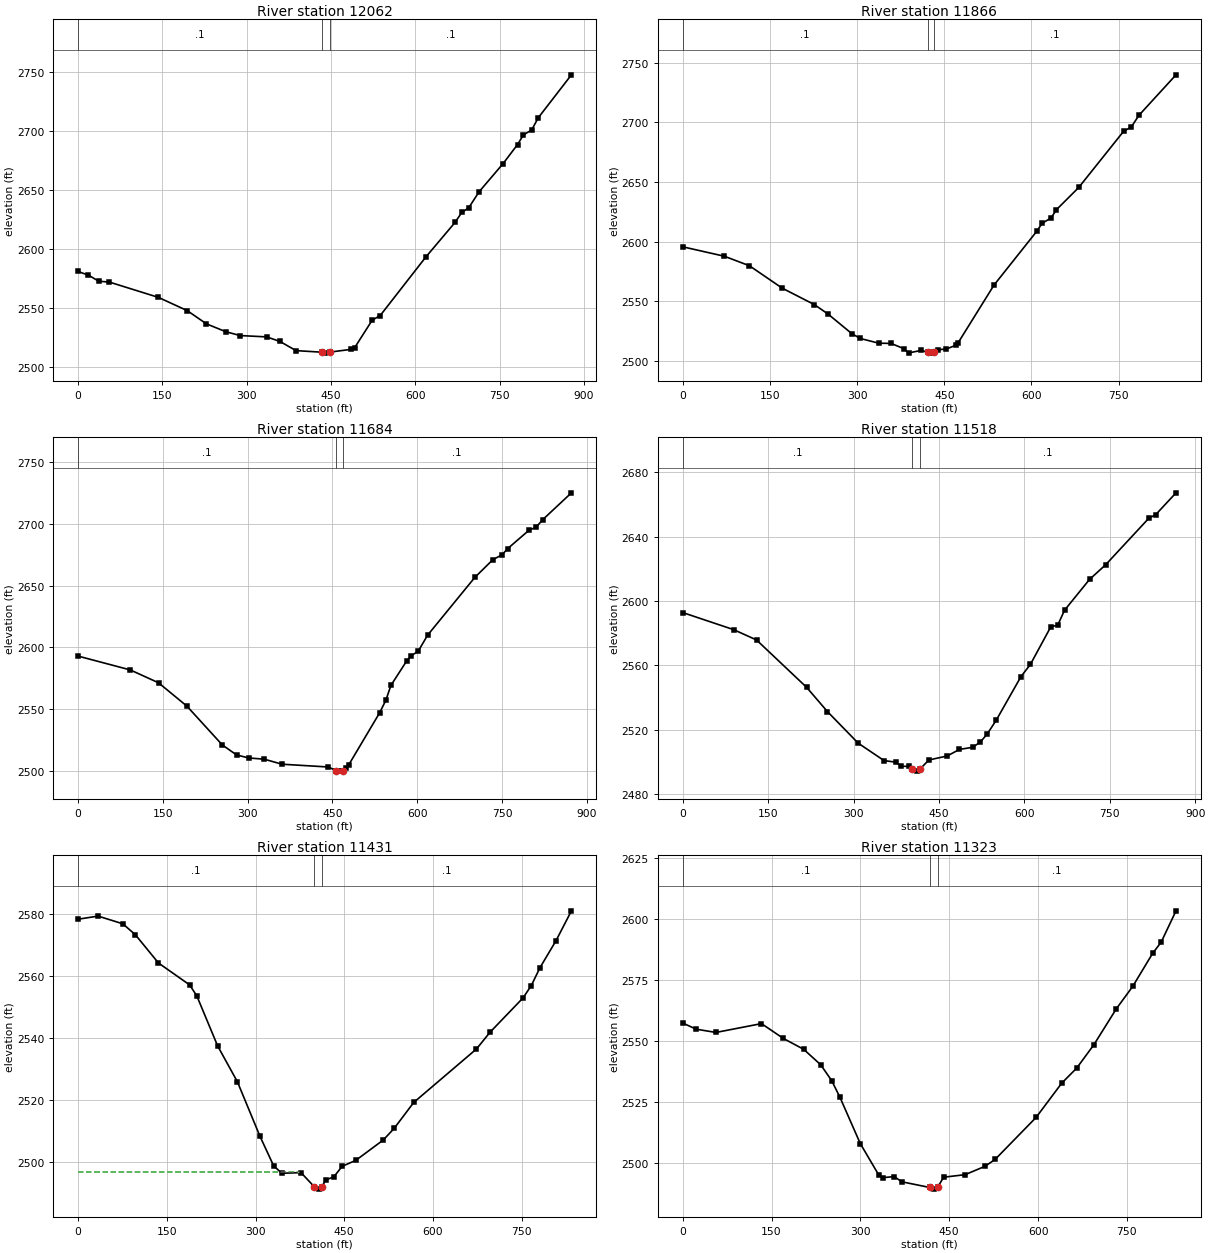
Type RM Length L Ch R = 1 ,12062   ,199.6,195.9,191.9
XS GIS Cut Line= 3
2420751.34688107556109.1634033732421084.10557252555981.909641224
     2421423.807       555585.99
#Sta/Elev= 30
       0 2581.19    18.4 2578.06      37 2572.93    55.6 2572.23   142.8 2559.28
   194.2 2548.04   228.4 2536.84   262.7  2530.2   288.4 2526.92   335.5 2525.79
   358.9    2522   387.9 2514.16   433.3 2512.85   439.4 2512.04   448.22512.927
   486.2 2515.24   492.2 2516.69   523.4 2539.96   537.6 2543.86   618.6 2593.33
   670.9  2622.8   682.7 2631.18     695 2635.02   713.4  2648.6   756.4 2672.64
     782 2688.69   792.5 2696.91   807.1 2701.02   818.9 2711.41   877.9 2747.77
#Mann= 3 ,-1 , 0
       0      .1       0   433.3    .045       0   448.2      .1       0
Bank Sta=433.3,448.2
XS Rating Curve= 0 ,0
Exp/Cntr=0.3,0.1

Type RM Length L Ch R = 1 ,11866   ,178.9,181.8,181.8
XS GIS Cut Line= 3
     2421097.458      556377.7862421265.94170631556090.621854966
     2421456.189      555611.225
#Sta/Elev= 30
       0 2595.58    71.8 2587.63   114.8 2579.66   171.2 2560.84   226.7 2546.96
   250.1 2539.06     291 2522.61   305.6 2518.56   337.1 2514.62   358.6 2514.39
   380.1 2510.06   388.7 2506.42   410.2 2508.52  421.45 2507.08   427.4 2506.25
   432.52507.041   439.7 2509.23   453.3 2509.59   470.5 2513.03   473.6 2514.73
   535.5 2563.36   609.1 2608.59   618.4 2615.32   633.8 2619.83     643 2626.75
   681.3 2645.39   758.8 2692.77   771.7 2696.13   784.9 2706.03   848.7 2740.04
#Mann= 3 ,-1 , 0
       0      .1       0  421.45    .045       0   432.5      .1       0
Bank Sta=421.45,432.5
XS Rating Curve= 0 ,0
Exp/Cntr=0.3,0.1

Type RM Length L Ch R = 1 ,11684   ,164.8,165.9,164.3
XS GIS Cut Line= 3
2421227.03686059556439.8256765772421464.08334753556002.789726796
     2421493.492      555628.289
#Sta/Elev= 30
       0 2593.03    92.3 2581.86   142.3 2571.47   192.4 2552.65   255.1 2521.28
   280.3 2513.19   301.6 2510.74   329.5 2509.73   360.7 2505.68   442.6 2503.43
   456.5 2500.55   465.2 2500.09   468.1 2500.45   474.5  2502.3     479 2505.31
   533.3 2547.07   544.5 2557.36   553.5 2569.39   581.5 2589.22   589.5 2593.43
   601.5 2596.81   618.5 2610.02   701.8 2656.54   733.9 2670.98   749.9 2674.81
     760 2679.85   798.1 2694.86   810.1 2697.07   822.2 2703.33   872.8 2724.94
#Mann= 3 ,-1 , 0
       0      .1       0   456.5    .045       0   468.1      .1       0
Bank Sta=456.5,468.1
XS Rating Curve= 0 ,0
Exp/Cntr=0.3,0.1

Type RM Length L Ch R = 1 ,11518   ,86.4,86.4,86.3
XS GIS Cut Line= 4
      2421241.38      556450.4472421504.15821374556220.182929294
2421590.63000429556074.7580369082421601.54513579555727.158836477
#Sta/Elev= 30
       0 2592.78    89.5 2582.15   129.7 2575.72   217.6 2546.27   254.3 2531.13
   308.2 2511.51   353.7 2500.65   374.3 2499.68   383.6 2497.19   397.5    2497
   402.62495.403   411.6  2494.1   417.12495.492   432.4 2501.04   464.6 2503.53
     486 2507.61   509.3 2508.93   522.6 2512.18   534.6 2517.08   550.6 2525.76
   594.2 2552.98   610.6 2560.47   646.6 2583.98   658.6  2584.9   670.6 2594.22
   714.5 2613.39   742.7 2622.48   818.7 2651.49   830.7 2653.69   866.4 2667.29
#Mann= 3 ,-1 , 0
       0      .1       0   402.6    .045       0   417.1      .1       0
Bank Sta=402.6,417.1
XS Rating Curve= 0 ,0
Exp/Cntr=0.3,0.1

Type RM Length L Ch R = 1 ,11431   ,107.6,108.3,108.8
XS GIS Cut Line= 2
     2421405.363      556559.996     2421826.907      555840.219
#Sta/Elev= 30
       0 2578.24    33.9 2579.23    75.6 2576.76    96.9 2573.23   135.9 2564.15
   188.6 2557.11   200.8 2553.55     236 2537.46   269.4 2525.94   307.4 2508.47
   330.7 2498.91   344.5 2496.53   376.9 2496.74   399.42492.183   406.7 2491.43
   412.6 2492.27   418.6 2494.37   432.5  2495.4   446.4 2498.76   469.6 2500.69
     516 2507.23   534.5 2510.99   567.5 2519.31   673.6 2536.51   696.7 2541.93
   752.4 2552.94   766.3 2556.91   780.9 2562.64     808 2571.31   834.1 2580.93
#Mann= 3 ,-1 , 0
       0      .1       0   399.4    .045       0   412.6      .1       0
#XS Ineff= 2 , 0
          373.54 2497.04
Permanent Ineff=
       F       F
Bank Sta=399.4,412.6
XS Rating Curve= 0 ,0
Exp/Cntr=0.3,0.1

Type RM Length L Ch R = 1 ,11323   ,162.5,163.3,163.8
XS GIS Cut Line= 3
     2421479.659      556597.788     2421711.787      556242.311
     2421937.182      555901.841
#Sta/Elev= 30
       0 2557.34    22.8  2554.8    56.2 2553.46     133 2557.09   170.1 2550.98
   204.3 2546.52     233 2540.19   251.5 2533.68   265.2 2526.98   299.8 2507.81
     331 2494.88   338.1 2493.79   357.2 2494.21   369.9 2492.08   417.12489.746
   424.6 2489.06   430.6 2489.91   440.6 2493.96   476.8    2495   510.4 2498.44
   527.5 2501.28   596.7 2518.54   639.9  2532.6   665.2  2538.8   694.2  2548.4
   732.2 2563.21   759.8 2572.38   793.4 2585.96   807.8 2590.57   832.9 2603.45
#Mann= 3 ,-1 , 0
       0      .1       0   417.1    .045       0   430.6      .1       0
Bank Sta=417.1,430.6
XS Rating Curve= 0 ,0
Exp/Cntr=0.3,0.1

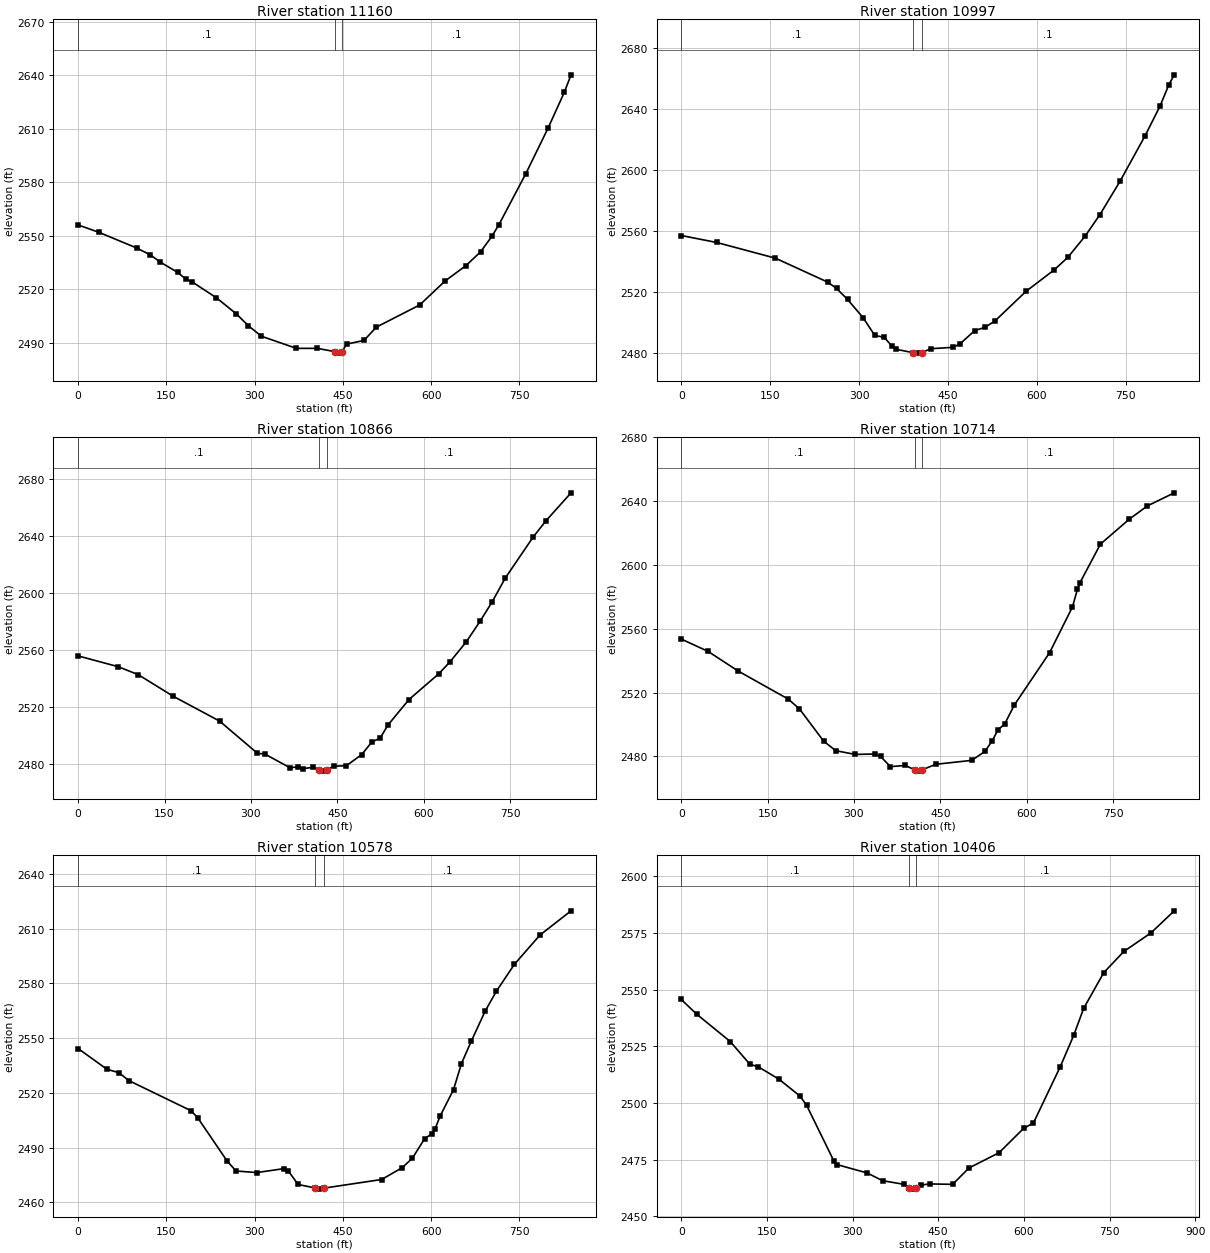
Type RM Length L Ch R = 1 ,11160   ,162.7,163.1,162.3
XS GIS Cut Line= 2
 2421586.3039554556663.5643085572422079.30570069 555986.20928807
#Sta/Elev= 30
       0 2555.98    35.7 2551.81    99.6 2543.05   122.5 2539.26   139.9  2535.1
   169.3 2529.37   182.7 2525.73   194.3 2523.94   235.1 2515.15   268.6 2506.23
   289.4  2499.5   311.5  2493.6     371  2486.8   406.7 2486.78   436.4 2484.97
   445.8 2484.12   448.72484.831   456.2 2489.18   485.9 2491.22   506.9 2498.69
   580.6 2511.13   623.6 2524.52     659 2533.14     684 2540.88   703.5 2549.73
   715.2 2556.11     761 2584.77   799.2 2610.57   826.4 2630.38   837.8 2640.12
#Mann= 3 ,-1 , 0
       0      .1       0   436.4    .045       0   448.7      .1       0
Bank Sta=436.4,448.7
XS Rating Curve= 0 ,0
Exp/Cntr=0.3,0.1

Type RM Length L Ch R = 1 ,10997   ,129.7,130.7,130.7
XS GIS Cut Line= 2
2421697.22044235556742.0090743292422205.43849257556083.700801124
#Sta/Elev= 30
       0 2556.91    59.8 2552.33   158.8 2542.03   247.2 2526.27   261.9 2522.17
   280.5 2514.93   306.7 2502.99   326.3 2491.38   342.7 2489.98   355.5  2484.2
   362.9 2482.16   390.92480.034   398.3 2479.69   405.8 2480.02   421.1  2482.6
   458.2 2483.48   469.6 2485.57   495.2 2494.54   512.4  2496.6   529.5 2500.92
   581.5 2520.22   629.3 2534.39   652.1 2542.56   681.3  2556.5   706.3 2570.63
   740.5 2592.72   782.3 2622.25   807.6 2641.81   822.7    2656   831.7  2662.4
#Mann= 3 ,-1 , 0
       0      .1       0   390.9    .045       0   405.8      .1       0
Bank Sta=390.9,405.8
XS Rating Curve= 0 ,0
Exp/Cntr=0.3,0.1

Type RM Length L Ch R = 1 ,10866   ,148.2,151.6,153.9
XS GIS Cut Line= 2
     2421771.371         556808.2422337.08761149556166.292198876
#Sta/Elev= 30
       0 2555.98    69.8  2548.4   104.7 2542.79   165.2 2527.71   245.5 2510.38
     311  2487.9   324.9 2487.11   367.4  2477.8   381.5 2478.22     391 2477.15
   407.1 2477.94   418.72476.324   426.9 2475.33   431.3 2476.25   443.4 2478.76
   465.6 2479.12   492.1 2486.87   509.9 2495.76   524.3  2498.4   537.4  2507.4
   574.2 2525.42   625.6 2543.33   645.1 2551.65   673.6 2565.77   697.4 2580.08
   718.8 2593.94   741.4 2610.48   789.6  2639.1   812.3  2650.7   855.5 2670.11
#Mann= 3 ,-1 , 0
       0      .1       0   418.7    .045       0   431.3      .1       0
Bank Sta=418.7,431.3
XS Rating Curve= 0 ,0
Exp/Cntr=0.3,0.1

Type RM Length L Ch R = 1 ,10714   ,137.2,136.3,135.5
XS GIS Cut Line= 3
      2421798.91      556841.7852422226.24737755556551.144774571
2422431.52058738556280.642821612
#Sta/Elev= 30
       0 2553.59    46.7 2545.82    98.8 2533.54   185.9 2515.93   205.2 2509.84
   247.3 2489.57   268.3  2483.6     302 2481.25   335.8 2481.51   346.1 2480.02
   363.3 2473.59   389.2 2474.32   406.5 2471.42   412.3 2470.77   418.62471.634
   442.2 2475.06   504.4 2477.51   527.4 2483.08   540.5 2489.95   550.2 2496.74
   561.6 2500.18   578.7  2512.3   639.8 2545.04   679.5 2573.71   688.1 2584.69
   692.7 2589.03   728.2 2613.16   778.5 2628.85   809.9 2637.13   856.4  2645.3
#Mann= 3 ,-1 , 0
       0      .1       0   406.5    .045       0   418.6      .1       0
Bank Sta=406.5,418.6
XS Rating Curve= 0 ,0
Exp/Cntr=0.3,0.1

Type RM Length L Ch R = 1 ,10578   ,172.6,171.9,171.4
XS GIS Cut Line= 3
     2421888.009      556974.8752422339.79709311556626.844584939
2422462.09835878556389.145005622
#Sta/Elev= 30
       0 2544.27    49.1 2532.89      69 2531.06    86.6 2526.64   191.7 2510.22
   203.1 2506.41   253.2 2482.64   268.3 2477.16   303.7 2476.29   349.1 2478.42
   357.1 2477.23   373.9 2469.76   402.4 2467.89   409.7 2467.22   417.42467.749
   515.7 2472.49   550.9    2479   568.1 2484.19   588.8 2494.86   600.7 2497.45
   606.4 2500.16   615.4 2507.41   637.9 2521.72   651.4 2536.03   668.1  2548.3
   691.9 2564.89   710.6 2575.58   741.4 2590.43   784.8 2606.43   837.6 2619.71
#Mann= 3 ,-1 , 0
       0      .1       0   402.4    .045       0   417.4      .1       0
Bank Sta=402.4,417.4
XS Rating Curve= 0 ,0
Exp/Cntr=0.3,0.1

Type RM Length L Ch R = 1 ,10406   ,156.3,154.7,154.9
XS GIS Cut Line= 3
     2422000.413      557136.3092422446.92512817556741.699115303
2422558.38232342556498.485646846
#Sta/Elev= 30
       0 2545.72    26.9 2539.25    85.7 2527.18   120.3  2517.1   134.5 2516.08
   171.1 2510.55   207.9  2503.1   219.5 2499.03   267.1 2474.55   272.5 2472.89
   325.8 2469.16   352.5 2465.77   389.5 2464.19   398.12462.527   405.9 2462.05
   411.2 2462.58   419.2 2463.84   434.8 2464.34   475.3 2464.16   503.8 2471.37
   556.7 2478.14   599.4 2488.81   616.8 2491.25   663.7 2516.04   687.2 2529.84
   704.8 2541.85     740 2557.59   775.2 2566.94   822.6  2575.1   863.4 2584.84
#Mann= 3 ,-1 , 0
       0      .1       0   398.1    .045       0   411.2      .1       0
Bank Sta=398.1,411.2
XS Rating Curve= 0 ,0
Exp/Cntr=0.3,0.1