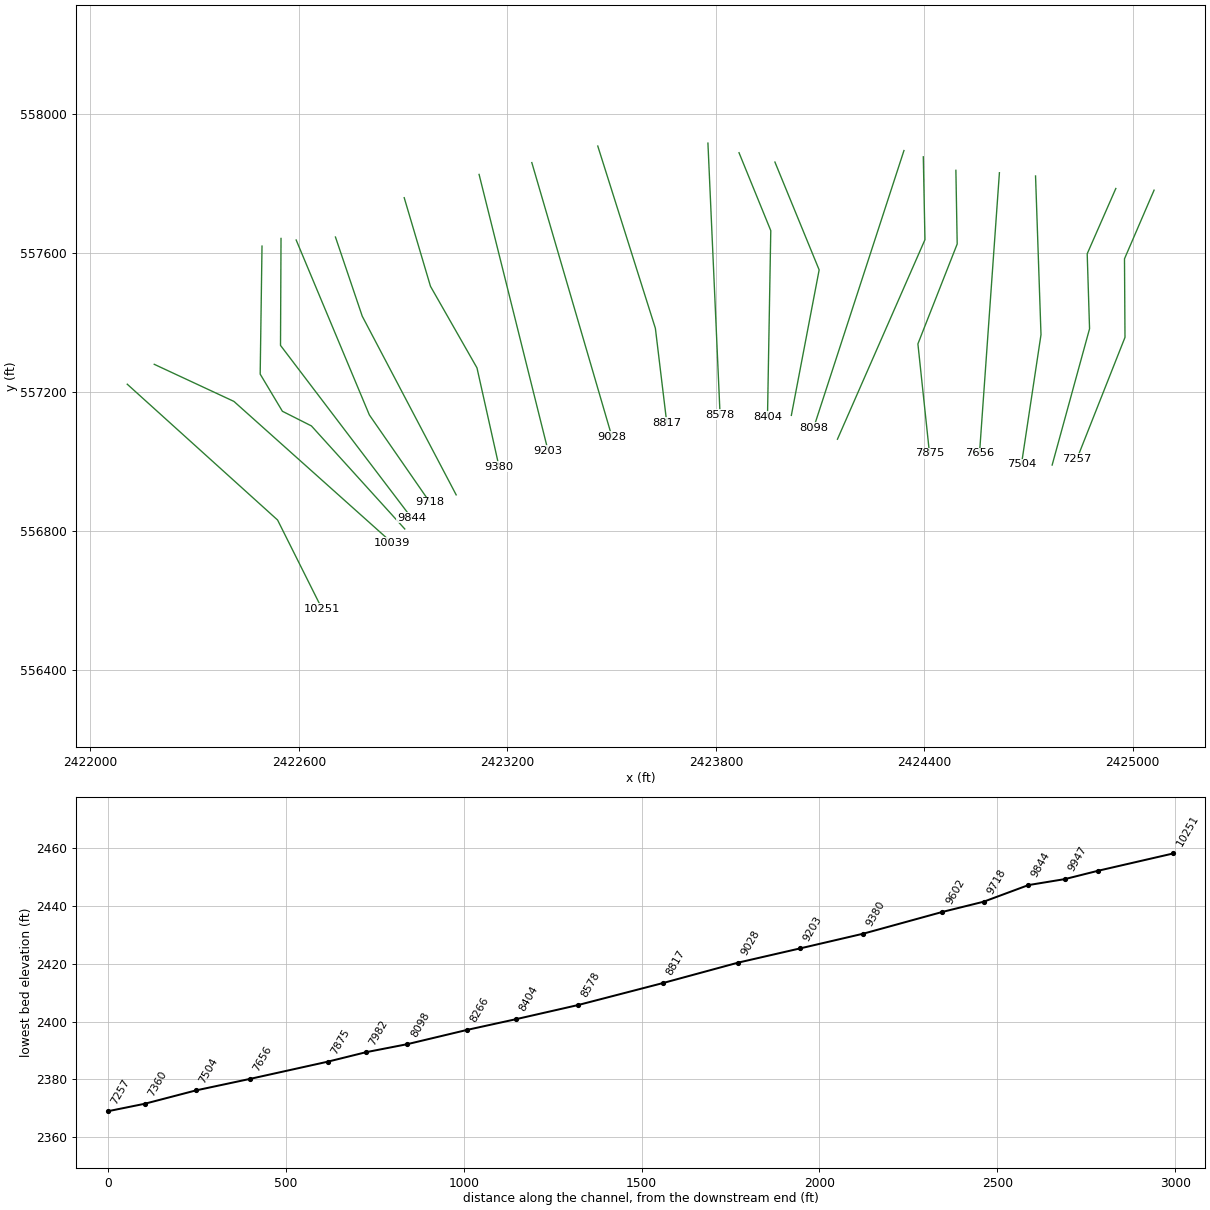
HEC-RAS study LONGRN1.prj: LONGRN1

--- LONGRN1.g01 (geometry) --- (continued)

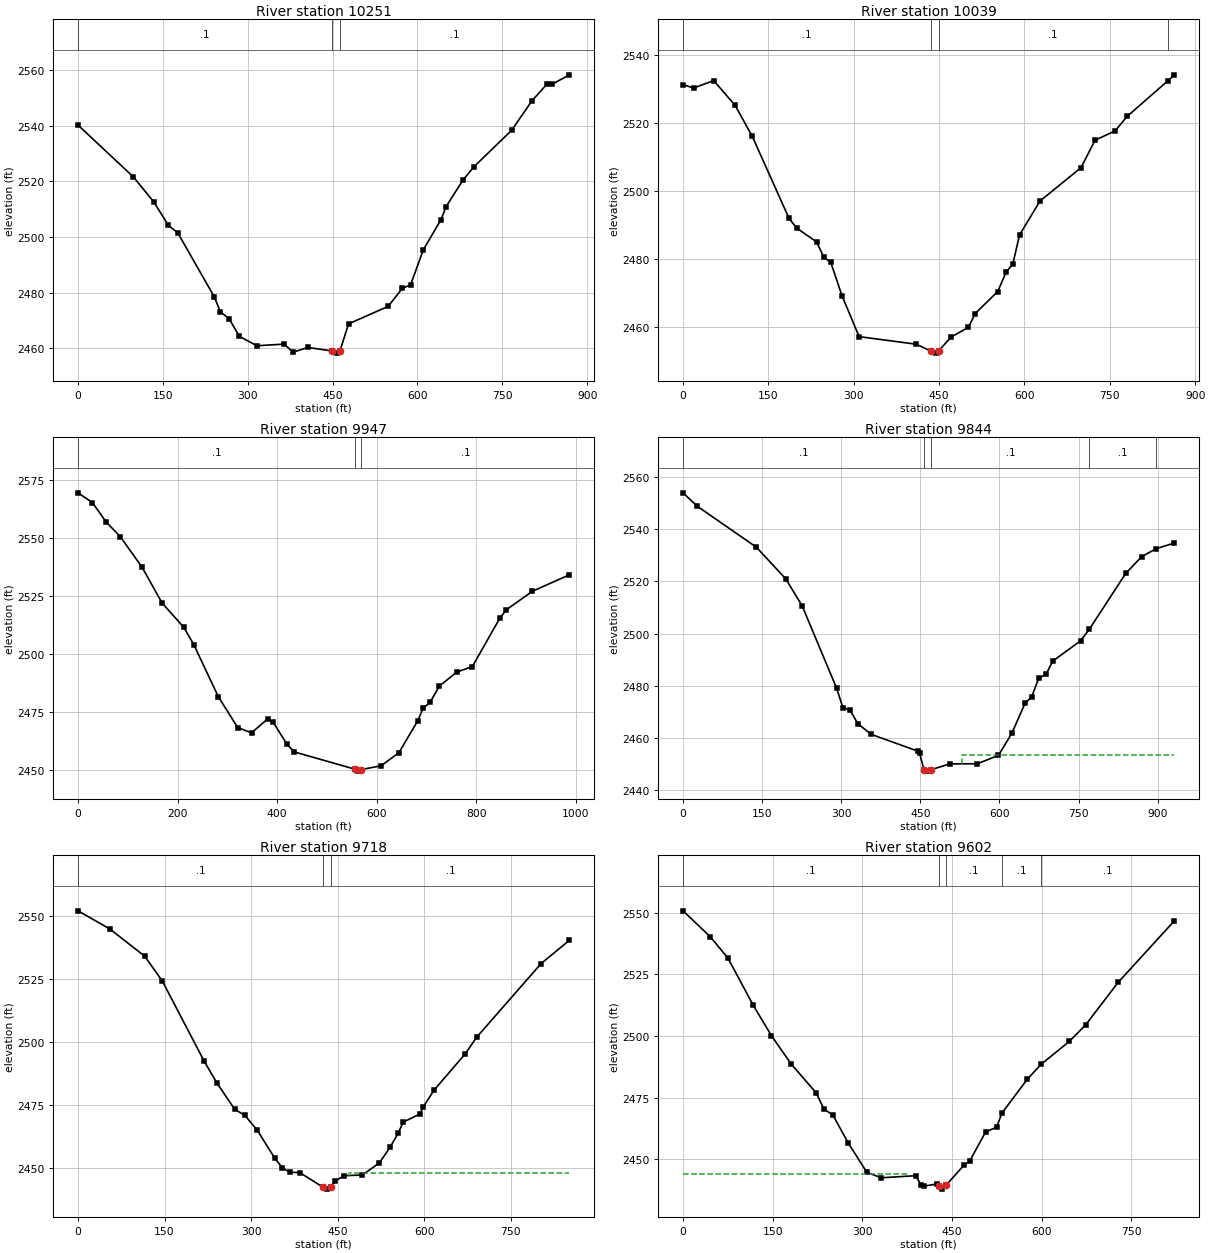
Type RM Length L Ch R = 1 ,10251   ,209.5,212.7,212.6
XS GIS Cut Line= 3
     2422105.911      557221.9422422538.57903898556830.757035353
     2422666.161      556575.703
#Sta/Elev= 30
       0 2540.16    97.7 2521.58   134.5 2512.41   159.9  2504.1   176.2  2501.5
   240.9 2478.45   251.6 2473.11   267.3 2470.55   285.2 2464.26   316.3 2460.91
   363.9  2461.5   380.6 2458.63   406.3  2460.3   448.8 2459.04   457.3 2458.26
     463 2459.05   478.1 2468.75   548.2 2475.06   573.4 2481.57   587.8 2482.75
   610.2 2495.33   641.5 2506.19   650.6  2510.9   680.2 2520.34   699.6 2525.15
   766.5  2538.3   802.2 2548.85   829.2 2554.94     838 2554.82   868.5  2558.2
#Mann= 3 ,-1 , 0
       0      .1       0   448.8    .045       0     463      .1       0
Bank Sta=448.8,463
XS Rating Curve= 0 ,0
Exp/Cntr=0.3,0.1

Type RM Length L Ch R = 1 ,10039   ,89,92.3,94.9
XS GIS Cut Line= 3
2422183.62017477557279.2084833232422412.88656519557172.405287249
2422867.97510968556765.192249094
#Sta/Elev= 30
       0 2531.22    18.7 2530.26      54 2532.43    91.5 2525.15   121.6 2516.05
   186.4 2491.85   199.8 2489.03   234.9 2484.93   247.6 2480.37   259.6 2478.99
   279.3 2469.14   309.5 2457.07   409.7 2454.85   435.2 2452.86   443.7 2452.22
   449.4 2452.95   471.5    2457   501.5 2459.81   513.5 2463.88     553 2470.34
   568.3 2476.22   579.5 2478.39   591.4 2487.02   627.4 2496.99   699.4 2506.81
   724.1 2514.89   759.4 2517.63   780.8 2521.95  851.712532.321   863.6 2534.13
#Mann= 4 ,-1 , 0
       0      .1       0   435.2    .045       0   449.4      .1       0
  851.71     .05       0
Bank Sta=435.2,449.4
XS Rating Curve= 0 ,0
Exp/Cntr=0.3,0.1

Type RM Length L Ch R = 1 ,9947    ,107.2,102.7,96.5
XS GIS Cut Line= 5
2422493.75712941557619.688867278  2422488.490165557251.001357976
2422552.43539806557143.9850892762422635.96516872557101.770699449
2422904.58035407  556805.0650372
#Sta/Elev= 30
       0 2569.33    28.8 2565.16    56.8 2556.71    84.8 2550.49   128.8 2537.25
   168.8 2521.87   212.8 2511.29   232.8  2503.8   281.8 2481.51   320.8 2468.14
   348.8 2465.86   380.9 2471.87   392.2  2470.4   419.9  2460.9   434.6 2457.63
   555.82450.232   563.2 2449.36     5692450.034     609 2451.67   644.8 2457.34
   682.6 2471.12   693.4  2476.5   707.1 2478.95   725.8 2485.97   760.9 2492.08
   792.1  2494.4   847.4 2515.28   860.7 2518.95     913 2526.91   987.2    2534
#Mann= 3 , 0 , 0
       0      .1       0   555.8    .045       0     569      .1       0
Bank Sta=555.8,569
XS Rating Curve= 0 ,0
Exp/Cntr(USF)=0,0
Exp/Cntr=0.3,0.1

Type RM Length L Ch R = 1 ,9844    ,128.5,125.8,122.3
XS GIS Cut Line= 3
2422548.47171193557641.7462137412422546.98962274557333.692715553
     2422924.084      556837.033
#Sta/Elev= 30
       0 2553.89    27.2 2548.73   139.1 2533.06   195.1 2520.85     226 2510.55
   291.1 2479.09   303.1 2471.62   316.9  2470.6   331.3 2465.46     357 2461.35
   445.5 2454.92   448.4 2454.24   456.9 2447.71   462.6 2447.28   470.72447.847
   505.5 2450.05     558 2450.11   598.1 2453.32   623.3 2461.76   648.4 2473.23
   661.2 2475.79   674.4 2482.91   688.1 2484.33   700.9 2489.41   753.8 2497.21
  770.282501.602   839.4 2523.04   869.3 2529.38  896.512532.461   931.7 2534.67
#Mann= 5 ,-1 , 0
       0      .1       0   456.9    .045       0   470.7      .1       0
  770.28      .1       0  896.51      .1       0
#XS Ineff= 2 , 0
                          529.67         2453.48
Permanent Ineff=
       F       F
Bank Sta=456.9,470.7
XS Rating Curve= 0 ,0
Exp/Cntr=0.3,0.1

Type RM Length L Ch R = 1 ,9718    ,115.1,115.6,116.6
XS GIS Cut Line= 3
2422592.07379856 557637.245415342422802.75237531 557133.37248596
2422976.56220112556882.313848673
#Sta/Elev= 30
       0 2552.03    54.9 2544.87   115.6 2534.01   146.1 2524.15   218.9 2492.21
   240.8 2483.66   271.6 2473.18     289 2470.85   310.7  2464.9     341 2453.78
   354.2 2449.97     367 2448.22   384.4 2448.08   424.2 2442.34     432 2441.52
   438.8 2442.52   445.6  2444.7   460.9 2446.85   492.7 2447.13   522.1  2451.9
   540.5 2458.06   555.1 2463.84   563.3  2468.1   592.5 2471.34   598.4 2474.28
   617.6 2481.01   671.1 2495.27   690.5 2501.76   802.4 2531.08   851.5 2540.32
#Mann= 3 , 0 , 0
       0      .1       0   424.2    .045       0   438.8      .1       0
#XS Ineff= 2 , 0
                          469.22         2447.78
Permanent Ineff=
       F       F
Bank Sta=424.2,438.8
XS Rating Curve= 0 ,0
Exp/Cntr(USF)=0,0
Exp/Cntr=0.3,0.1

Type RM Length L Ch R = 1 ,9602    ,222.1,222.4,222.8
XS GIS Cut Line= 3
     2422705.125      557645.7992422782.24943302557417.777086374
2423052.60367096556903.223765771
#Sta/Elev= 30
       0  2550.8    45.6  2540.3    75.2 2531.62   117.4 2512.54   147.9 2500.19
   180.7 2488.77     223 2476.94   235.6 2470.48   250.7 2468.04   275.9 2456.88
   307.5  2444.8   331.6 2442.59   388.9 2443.43   397.9 2439.83   402.4 2439.17
     425  2440.1   428.4 2439.36     434 2437.99   440.2 2439.61   470.2 2447.78
   479.2 2449.22   506.3 2461.22   524.4 2463.06  533.372468.784     576 2482.58
   599.22488.637   646.4 2497.92   673.5 2504.58   727.7 2521.77     822 2546.78
#Mann= 5 ,-1 , 0
       0      .1       0   428.4    .045       0   440.2      .1       0
  533.37      .1       0   599.2      .1       0
#XS Ineff= 2 , 0
          375.55 2443.95
Permanent Ineff=
       F       F
Bank Sta=428.4,440.2
XS Rating Curve= 0 ,0
Exp/Cntr=0.3,0.1

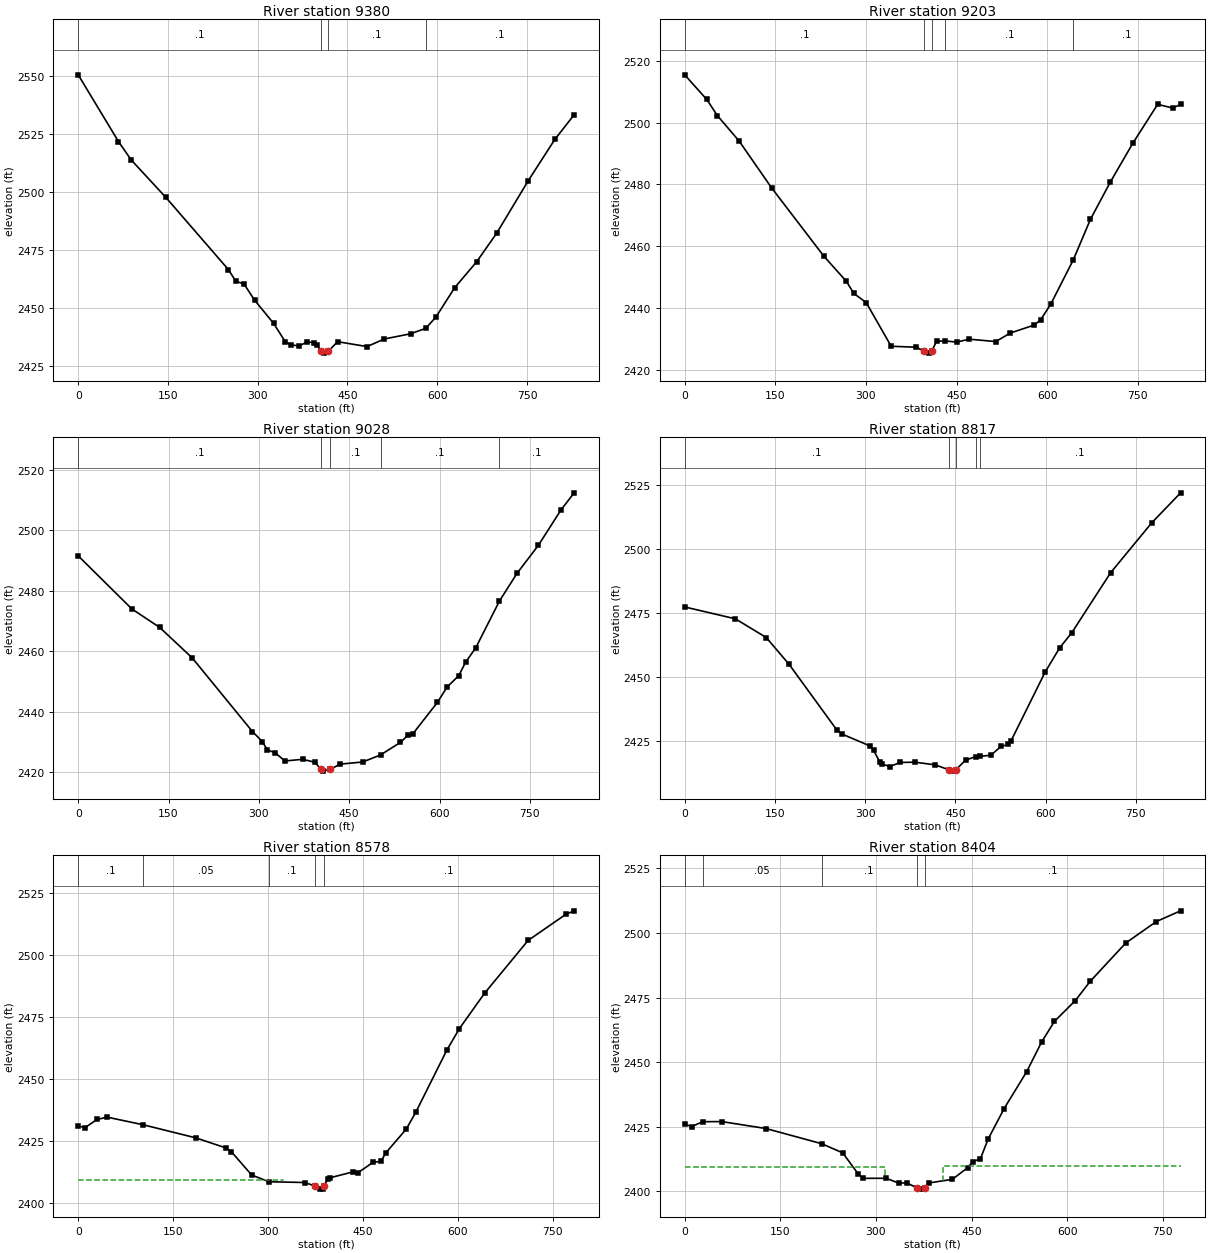
Type RM Length L Ch R = 1 ,9380    ,179.8,177.1,173.8
XS GIS Cut Line= 4
2422902.98161149 557759.126552032422978.64902049557503.817730418
2423112.45722652557268.9878039262423176.13852792556983.808109681
#Sta/Elev= 30
       0 2550.66    67.3 2521.83    88.5 2513.92   146.5  2497.7   250.9 2466.56
   263.4 2461.49   276.9 2460.38   294.9 2453.29   326.6 2443.27   345.9 2435.43
   355.1 2434.04     369 2433.57   382.8 2435.28   394.6 2434.97   399.3 2434.11
  405.61 2431.21   410.4 2430.45   417.72431.167   433.4  2435.4   482.6 2433.28
   511.7 2436.57   555.4 2438.81  580.882441.174   597.7 2445.99   629.1  2458.7
   665.9 2469.93   699.4 2482.28   752.1 2504.94   796.5 2522.74   828.8 2533.42
#Mann= 4 ,-1 , 0
       0      .1       0  405.61    .045       0   417.7      .1       0
  580.88      .1       0
Bank Sta=405.61,417.7
XS Rating Curve= 0 ,0
Exp/Cntr=0.3,0.1

Type RM Length L Ch R = 1 ,9203    ,174.5,174.8,175.9
XS GIS Cut Line= 2
2423118.52238289557826.1261691442423317.14038289557029.867169144
#Sta/Elev= 30
       0 2515.53    36.6 2507.54      54 2502.35    90.2 2494.05   143.8 2478.92
   230.4 2456.74   267.5 2448.65   279.8 2444.73   300.5 2441.71   341.7 2427.58
   382.9 2427.29   396.72425.956   403.7 2425.36   408.6    2426   416.9 2429.17
  431.49 2429.32   449.9 2428.92   470.8 2429.88   514.8 2429.11     539 2431.88
   578.6 2434.46     589 2436.14   605.5 2441.12  643.132455.591   671.4 2468.69
   704.4 2480.79   741.5 2493.33   782.7 2505.97   807.5 2504.77   820.7 2505.94
#Mann= 5 ,-1 , 0
       0      .1       0   396.7    .045       0   408.6      .1       0
  431.49      .1       0  643.13      .1       0
Bank Sta=396.7,408.6
XS Rating Curve= 0 ,0
Exp/Cntr=0.3,0.1

Type RM Length L Ch R = 1 ,9028    ,211.3,211.2,210.8
XS GIS Cut Line= 2
2423270.30838289557860.1838457222423501.16538289557069.674845721
#Sta/Elev= 30
       0 2491.58    89.2 2474.01   135.3 2467.92   189.2 2457.87   289.2 2433.51
   305.8 2430.17   314.2 2427.37   326.7 2426.53   343.3 2423.76   372.5 2424.32
   393.2 2423.35   402.9 2420.99   405.8 2420.41   418.3    2421   435.2 2422.73
   472.5 2423.43  502.072425.776     535  2429.9   547.5 2432.27   555.8 2432.78
   596.4 2443.13   612.5  2448.2   631.9 2451.98   643.3 2456.45     660 2461.14
  699.472476.655   728.6 2485.79   763.9 2495.02   801.7 2506.78   823.5 2512.42
#Mann= 5 ,-1 , 0
       0      .1       0   402.9    .045       0   418.3      .1       0
  502.07      .1       0  699.47      .1       0
Bank Sta=402.9,418.3
XS Rating Curve= 0 ,0
Exp/Cntr=0.3,0.1

Type RM Length L Ch R = 1 ,8817    ,241,238.4,234.8
XS GIS Cut Line= 3
2423460.12672117557907.8720297312423625.92767658557382.888408995
2423658.68696102 557111.09281599
#Sta/Elev= 30
       0 2477.43    84.2  2472.8   135.6 2465.49   173.3  2455.1   253.1 2429.34
   261.4 2427.82   307.6 2423.21   314.2 2421.41   324.3 2416.85   328.5 2416.06
   341.1 2415.12   357.9 2416.72   383.1 2416.83   416.6 2415.77   439.3 2413.85
     446 2413.34   450.2 2413.79   466.9 2417.59  483.642419.025  490.332419.106
   508.9 2419.55   525.7 2422.97   538.2 2423.75   542.4 2425.14   599.2 2452.05
   623.3 2461.47   643.5 2467.41   707.9 2490.77   776.4  2510.3   824.3 2521.98
#Mann= 5 ,-1 , 0
       0      .1       0   439.3    .045       0   450.2      .1       0
  483.64      .1       0  490.33      .1       0
Bank Sta=439.3,450.2
XS Rating Curve= 0 ,0
Exp/Cntr=0.3,0.1

Type RM Length L Ch R = 1 ,8578    ,174.6,174.1,173.2
XS GIS Cut Line= 2
2423777.17635315557916.2702490942423812.16284572557133.483676577
#Sta/Elev= 30
       0 2431.13      11 2430.54    29.7 2433.78    45.7 2434.72  102.242431.674
   185.9 2426.37   233.1 2422.34   241.9 2420.82     274 2411.42  301.212408.701
     358 2408.38   374.72406.927     382 2405.72     386 2405.92   388.72407.158
   394.1 2409.68   398.1  2410.3   434.1 2412.68   442.1 2412.34   466.1 2416.56
   478.1 2416.88   486.1 2420.34   518.3 2429.91   533.6 2436.81   582.2 2461.62
   602.2 2470.36   642.3 2484.73   710.8 2505.91   770.4 2516.43   783.6 2517.85
#Mann= 5 ,-1 , 0
       0      .1       0  102.24     .05       0  301.21      .1       0
   374.7    .045       0   388.7      .1       0
#XS Ineff= 2 , 0
          322.96 2409.26
Permanent Ineff=
       F       F
Bank Sta=374.7,388.7
XS Rating Curve= 0 ,0
Exp/Cntr=0.3,0.1

Type RM Length L Ch R = 1 ,8404    ,133.3,138.4,142.5
XS GIS Cut Line= 3
2423866.66985835557888.5865506422423958.06181322 557664.30903585
2423948.61464515557128.636248248
#Sta/Elev= 30
       0 2426.03    10.8 2425.07   28.532426.943    58.3 2426.98   127.4  2424.3
  214.822418.424   247.9 2414.87   271.9  2406.8   279.9 2405.01   315.9 2405.03
   335.9 2403.16   348.1 2403.27   363.9 2401.37   371.9 2400.83   376.6 2401.42
   383.9 2403.25   419.9 2404.62   443.9 2409.16   451.9 2411.47   463.9 2412.58
   475.9 2420.18     501    2432   536.4 2446.28   559.9 2457.81   579.9 2465.75
   612.8 2473.86   635.9 2481.24   691.9 2496.14   739.9 2504.45   777.9 2508.59
#Mann= 5 ,-1 , 0
       0      .1       0   28.53     .05       0  214.82      .1       0
   363.9    .045       0   376.6      .1       0
#XS Ineff= 2 , 0
          313.63 2409.43  405.44         2409.66
Permanent Ineff=
       F       F
Bank Sta=363.9,376.6
XS Rating Curve= 0 ,0
Exp/Cntr=0.3,0.1

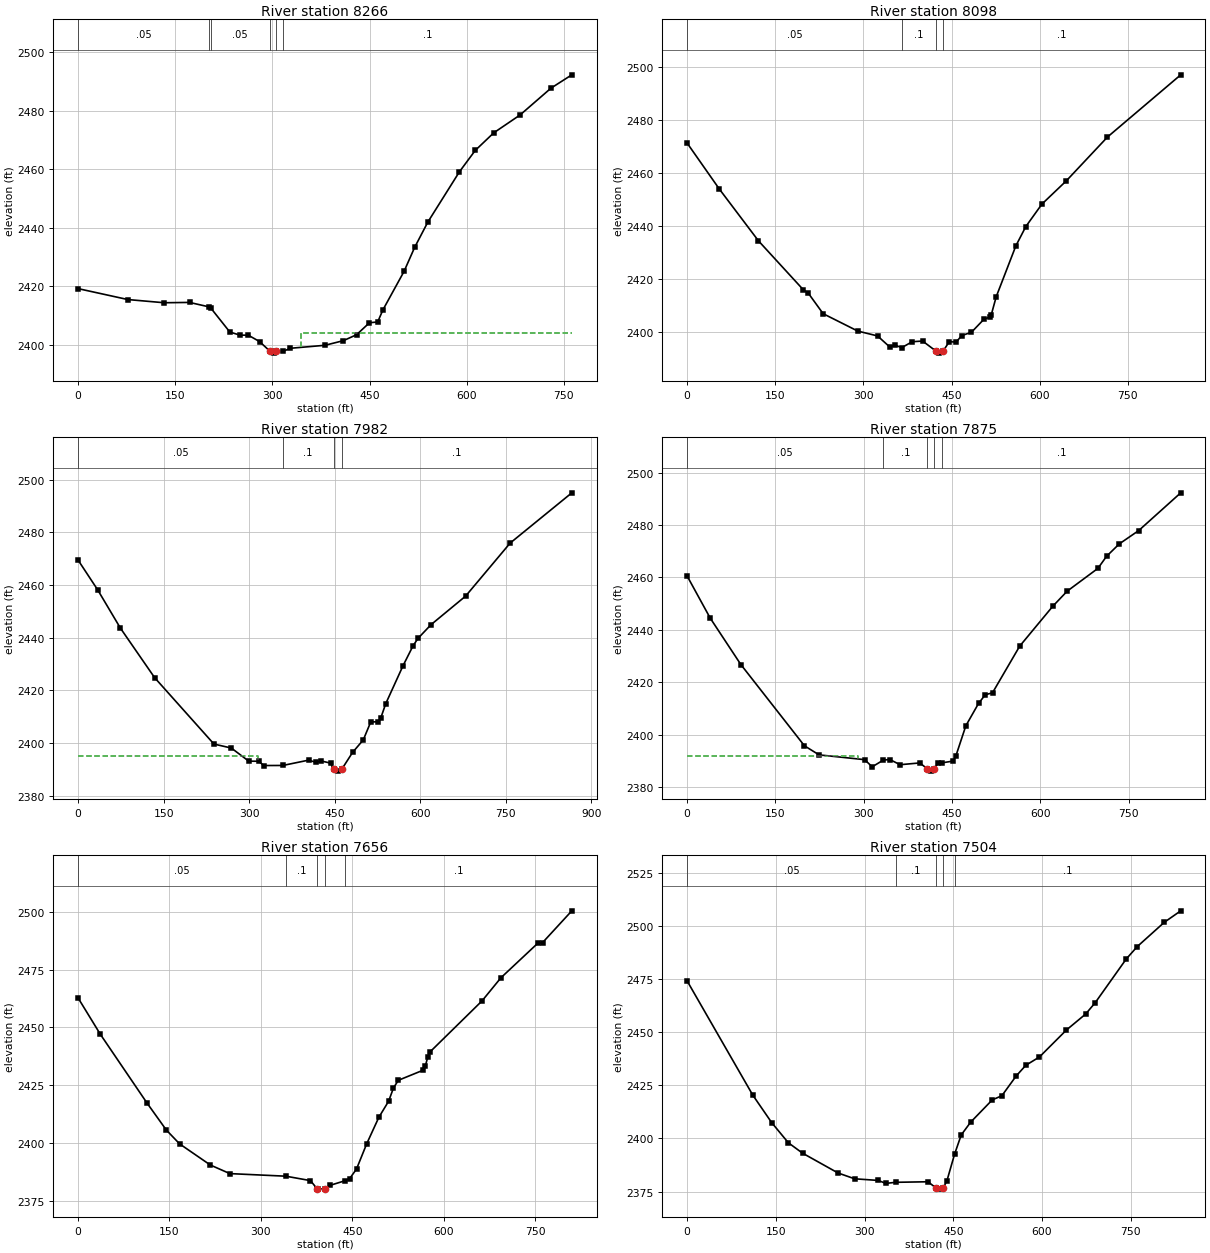
Type RM Length L Ch R = 1 ,8266    ,175.5,167.5,162.1
XS GIS Cut Line= 3
2423969.97475175557861.7750925812424097.27985528557551.194376679
2424017.27138289557132.205187938
#Sta/Elev= 30
       0 2419.16    76.9 2415.42   132.9 2414.33     172 2414.44  202.662412.893
  205.222412.417   234.2 2404.32   249.8 2403.25   262.8 2403.22   280.2 2401.04
   295.6 2397.86   301.7 2397.09     306 2397.76  316.592397.702   327.7 2398.75
   381.1 2399.77   409.6 2401.36   429.9 2403.39   449.8 2407.49   462.5 2407.75
   470.6  2411.9   503.2 2425.06   519.5 2433.25   539.9 2441.93   588.7 2459.15
   613.1 2466.45   641.6 2472.46   682.3 2478.58   730.1 2487.77   762.2 2492.32
#Mann= 6 ,-1 , 0
       0     .05       0  202.66      .1       0  205.22     .05       0
   295.6    .045       0     306     .05       0  316.59      .1       0
#XS Ineff= 2 , 0
                          344.51            2404
Permanent Ineff=
       F       F
Bank Sta=295.6,306
XS Rating Curve= 0 ,0
Exp/Cntr=0.3,0.1

Type RM Length L Ch R = 1 ,8098    ,117.6,116.6,115.3
XS GIS Cut Line= 2
2424341.34097897557894.8581949482424081.34376577557096.154429176
#Sta/Elev= 30
       0 2471.43      55 2454.03   121.6 2434.49     198 2416.02   206.4 2414.75
   231.6 2407.03   290.5 2400.48   324.2 2398.64   345.2 2394.43   353.2 2395.22
  365.43 2394.24   383.1 2396.46   400.8 2396.72     423 2393.03   429.3 2392.16
   435.7 2392.91   446.2 2396.49     458 2396.31   467.2 2398.76     484 2400.04
     505  2404.9   515.1  2405.8   517.7 2406.67   526.1 2413.44   559.5 2432.62
   576.5 2439.91   603.9 2448.38   645.2  2457.1   715.4 2473.66     840 2497.11
#Mann= 4 ,-1 , 0
       0     .05       0  365.43      .1       0     423    .045       0
   435.7      .1       0
Bank Sta=423,435.7
XS Rating Curve= 0 ,0
Exp/Cntr=0.3,0.1

Type RM Length L Ch R = 1 ,7982    ,106,106.6,108.5
XS GIS Cut Line= 3
2424397.05023423557876.8383828862424401.81932228557638.205652964
2424149.96407433557063.521368867
#Sta/Elev= 30
       0 2469.43    34.3 2458.16    74.3 2443.59   134.3 2424.81   238.3 2399.63
   268.8 2398.12   299.4 2393.14   316.9 2393.11   325.6 2391.48   359.1 2391.51
   404.2 2393.52   417.3 2392.71     426 2393.23   442.9  2392.4   448.12390.171
   456.6 2389.36   463.32390.328   481.5 2396.46   500.3 2401.22   513.4 2408.04
   526.5 2408.07   530.8 2409.41   539.6 2414.92   570.1  2429.4   587.6 2436.92
   596.3 2439.74     619 2444.91   679.8 2455.77   757.9 2475.89   866.1 2494.96
#Mann= 4 ,-1 , 0
       0     .05       0   359.1      .1       0   448.1    .045       0
   463.3      .1       0
#XS Ineff= 2 , 0
          314.96 2395.12
Permanent Ineff=
       F       F
Bank Sta=448.1,463.3
XS Rating Curve= 0 ,0
Exp/Cntr=0.3,0.1

Type RM Length L Ch R = 1 ,7875    ,214,218.7,220.6
XS GIS Cut Line= 4
     2424490.829      557837.984 2424494.5853969 557625.78761989
2424381.51669115557338.0167497792424414.90016969557022.768684433
#Sta/Elev= 30
       0 2460.64    39.4 2444.49    91.4 2426.78   199.4 2395.77   224.3  2392.3
   301.6 2390.48   314.5 2387.74  333.532390.347   344.6 2390.51   361.8 2388.55
   395.4 2389.23   407.7 2387.03   413.9  2386.1   419.2 2386.91   426.2 2389.06
  433.482389.285     452 2389.94   456.3 2391.72   473.5 2403.41     495 2411.91
   506.4 2415.23   518.8    2416     565 2433.81     621 2448.98   645.5 2454.76
   697.8 2463.48   712.5 2468.09     734  2472.8   767.1 2477.91   838.4  2492.3
#Mann= 5 ,-1 , 0
       0     .05       0  333.53      .1       0   407.7    .045       0
   419.2      .1       0  433.48      .1       0
#XS Ineff= 2 , 0
          290.49 2391.93
Permanent Ineff=
       F       F
Bank Sta=407.7,419.2
XS Rating Curve= 0 ,0
Exp/Cntr=0.3,0.1

Type RM Length L Ch R = 1 ,7656    ,151.9,152.7,153.8
XS GIS Cut Line= 2
2424616.10246422557831.0348120622424558.79928753557022.703134638
#Sta/Elev= 30
       0 2462.76    36.5 2447.06   112.7  2417.5   144.8 2405.68   166.6 2399.69
     217 2390.56   249.1 2386.84  341.03 2385.72   381.4 2383.81   392.32380.281
   393.4 2380.13   405.32380.296   413.5 2381.76  438.892383.821   445.8 2384.71
     457 2388.82   473.6 2399.66   493.6 2411.15   509.7 2418.14   517.7  2423.9
   525.7 2427.18   565.8 2431.48   569.8 2433.17   573.8  2437.1   577.8 2439.48
     663 2461.49   694.1 2471.51   754.3 2486.36   762.3 2486.66   810.4 2500.43
#Mann= 5 ,-1 , 0
       0     .05       0  341.03      .1       0   392.3    .045       0
   405.3      .1       0  438.89      .1       0
Bank Sta=392.3,405.3
XS Rating Curve= 0 ,0
Exp/Cntr=0.3,0.1

Type RM Length L Ch R = 1 ,7504    ,144.2,143.6,143.3
XS GIS Cut Line= 3
     2424720.105      557821.6452424735.78802103557364.441549795
     2424679.621      556991.716
#Sta/Elev= 30
       0 2474.28   111.1 2420.43   143.1 2407.45   171.2 2397.97   195.2 2393.07
   255.2 2383.73   283.2 2380.99   323.2 2380.21   335.9 2378.82  352.782379.334
   407.3 2379.59   421.5 2376.52   427.3 2376.12     4332376.683   439.3 2380.09
  452.062392.468   463.4 2401.63   479.3 2407.64   515.9 2418.16   532.1 2420.11
   556.4 2429.45   572.6 2434.45   595.7 2438.39   641.3 2451.09   673.7 2458.59
   689.9 2463.94   742.4 2484.56   760.9 2490.36   806.6  2501.8   834.4 2507.21
#Mann= 5 ,-1 , 0
       0     .05       0  352.78      .1       0   421.5    .045       0
     433      .1       0  452.06      .1       0
Bank Sta=421.5,433
XS Rating Curve= 0 ,0
Exp/Cntr=0.3,0.1

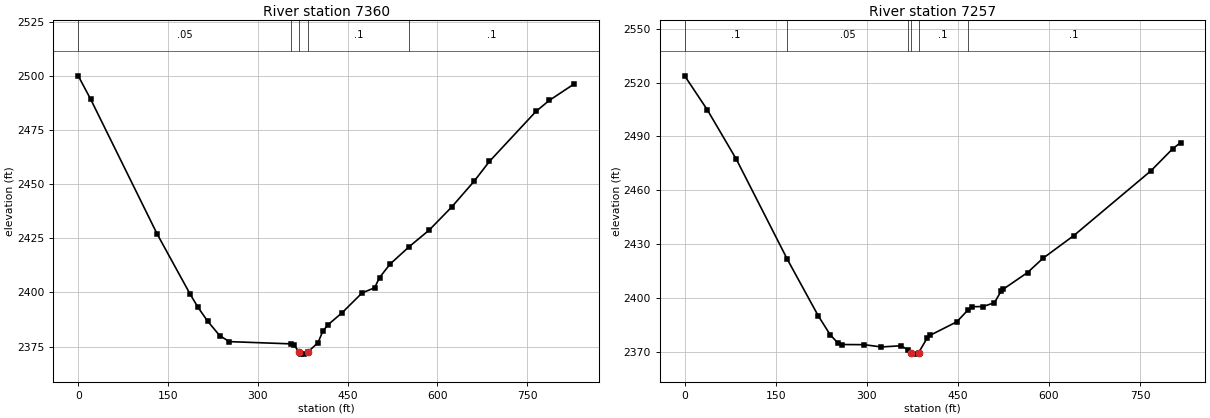
Type RM Length L Ch R = 1 ,7360    ,103.9,103.6,103
XS GIS Cut Line= 4
2424951.14924401 557785.627113612424868.77983835557597.600390698
2424875.54808134  557381.71105332424767.90177701556989.156556805
#Sta/Elev= 30
       0 2500.14    20.8 2489.32     132 2426.94   186.7 2399.34   199.8 2393.23
   216.3 2386.68   236.3 2380.06   252.3 2377.28  355.83 2376.24   360.3 2375.55
     369 2372.67   372.3 2371.63   376.3  2371.5   383.82372.559   400.4 2376.76
   408.4 2381.97   416.4 2384.87   441.1 2390.73   474.2 2399.81     495 2402.15
   503.3  2406.9   520.8  2413.1  552.852421.183   586.2 2428.84   623.5 2439.42
   660.9  2451.3   686.8 2460.58   764.5 2483.68   786.7 2488.77   828.3 2496.38
#Mann= 5 ,-1 , 0
       0     .05       0  355.83      .1       0     369    .045       0
   383.8      .1       0  552.85      .1       0
Bank Sta=369,383.8
XS Rating Curve= 0 ,0
Exp/Cntr=0.3,0.1

Type RM Length L Ch R = 1 ,7257    ,131.8,132.3,132.4
XS GIS Cut Line= 4
 2425061.2453436557780.8004221672424976.09374576557583.098511317
 2424977.5439337557356.8691929752424839.65703227557007.856812062
#Sta/Elev= 30
       0 2523.73    37.3  2504.8    85.2 2477.24  168.852421.793   219.9 2390.27
   239.7 2379.67   251.7 2375.33   259.8 2374.25   295.8 2374.17   323.7  2372.9
   355.7 2373.54  367.332371.462   373.42369.726   379.7 2368.91  385.18 2369.67
   399.7 2378.04   403.7  2379.3   448.2 2386.89  466.422393.424     474 2395.29
   491.2 2395.38   510.2 2397.51   521.1 2403.95   524.3 2404.96   564.7  2414.3
   590.1 2422.23   640.9 2434.86   767.9 2470.88   804.1 2483.28   816.8 2486.56
#Mann= 6 ,-1 , 0
       0      .1       0  168.85     .05       0  367.33      .1       0
   373.4    .045       0  385.18      .1       0  466.42      .1       0
Bank Sta=373.4,385.18
XS Rating Curve= 0 ,0
Exp/Cntr=0.3,0.1