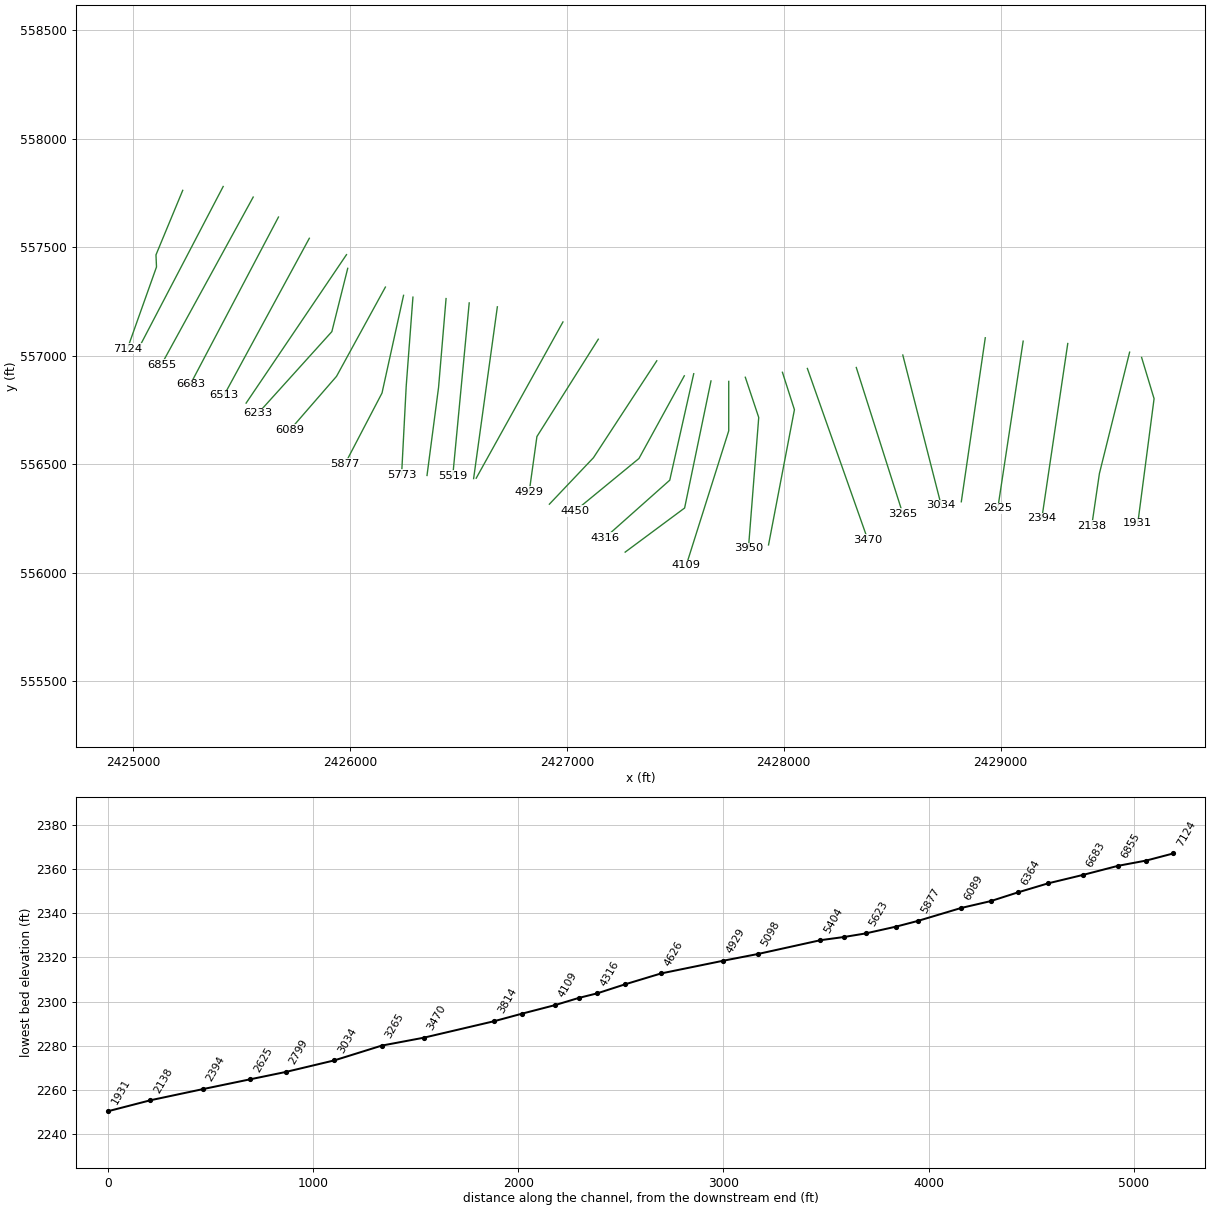
HEC-RAS study LONGRN1.prj: LONGRN1

--- LONGRN1.g01 (geometry) --- (continued)

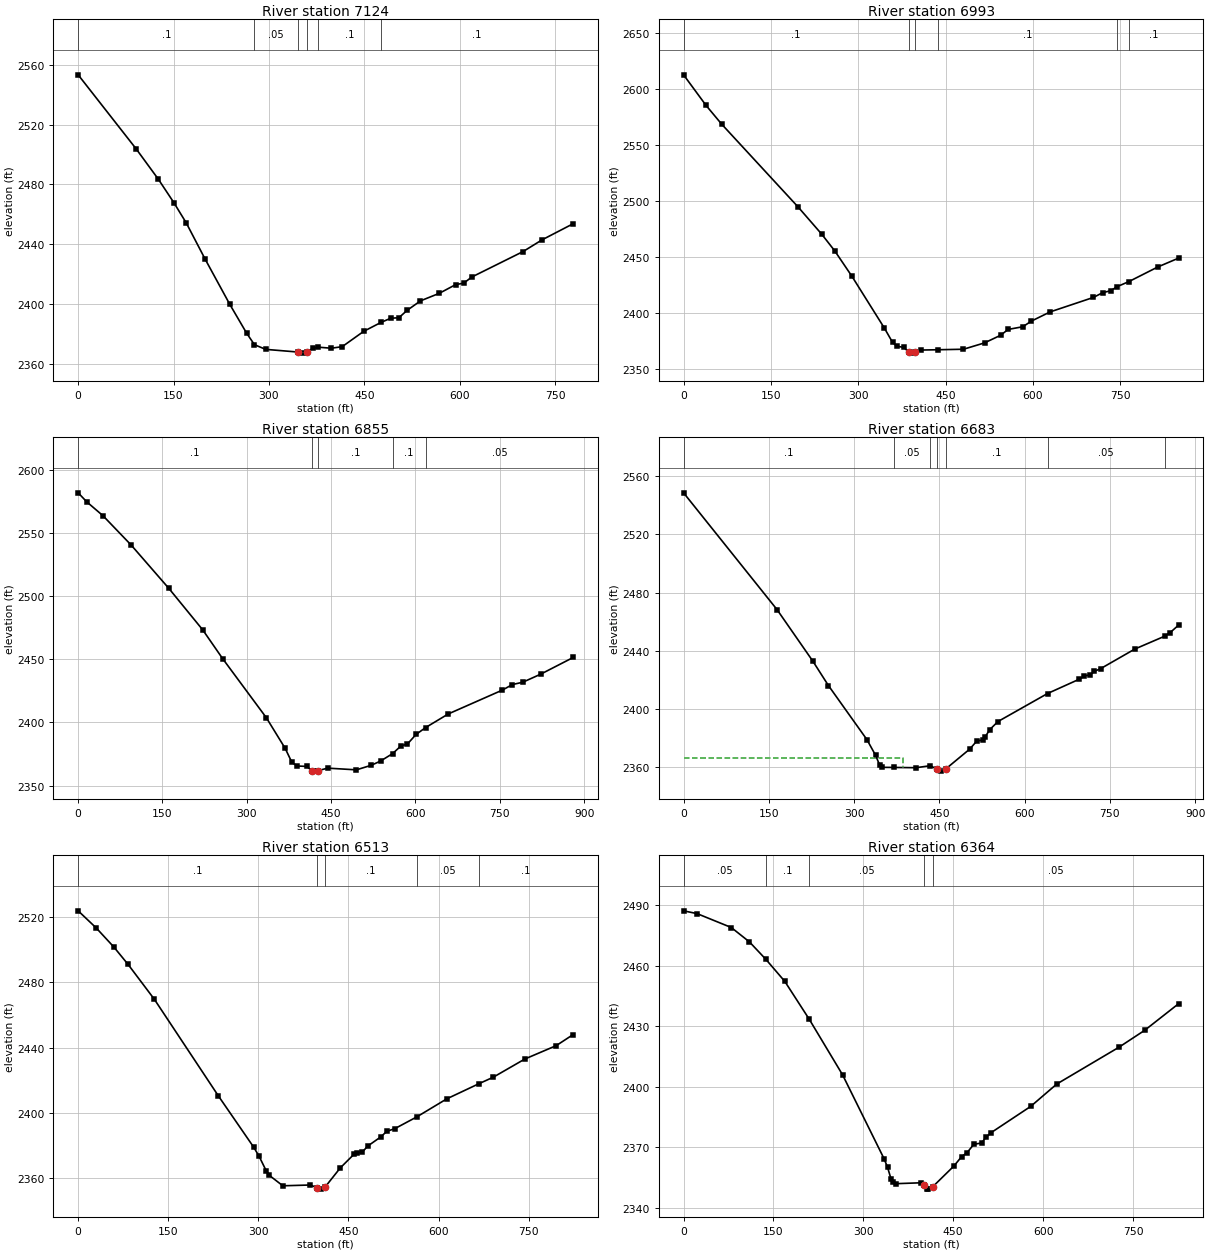
Type RM Length L Ch R = 1 ,7124    ,135.4,131.6,125
XS GIS Cut Line= 4
2425229.88185412557762.9388513432425106.61066019557465.633288332
     2425108.971557409.8318050522424974.76897897557032.507819071
#Sta/Elev= 30
       0 2553.38    91.3 2503.73     126 2483.51   150.5 2467.77   169.9 2454.25
   199.6 2429.99   238.5 2399.61   264.7 2380.51  277.13 2372.69   294.8 2369.56
   345.5 2367.77   352.9 2367.04  359.48  2367.9   368.9 2370.18  376.992371.039
   398.1 2370.33   415.1 2371.36     449 2381.65  476.252387.631   491.5 2390.41
   504.2 2390.73     517 2395.62   538.2 2402.04   567.9 2407.11   593.4  2412.9
   606.2 2413.89   618.7 2417.96   699.5 2435.05   729.2 2442.86   778.2 2453.68
#Mann= 6 ,-1 , 0
       0      .1       0  277.13     .05       0   345.5    .045       0
  359.48     .05       0  376.99      .1       0  476.25      .1       0
Bank Sta=345.5,359.48
XS Rating Curve= 0 ,0
Exp/Cntr=0.3,0.1

Type RM Length L Ch R = 1 ,6993    ,137.9,137.8,137.5
XS GIS Cut Line= 2
2425416.35291866557780.7740070092425022.73691866557027.225007009
#Sta/Elev= 30
       0 2612.58    38.6 2585.24    65.6 2568.39   196.5 2494.58   237.1 2470.26
   259.7  2455.2   289.2 2432.48     345 2386.13     359  2373.4   366.3 2369.98
   378.2 2368.98     387 2364.65   390.5 2363.83   396.92364.514   408.6 2366.59
  436.182366.841   480.8 2367.31   516.9 2372.98   544.5 2379.78   557.5 2385.02
   582.7 2387.41   597.5 2392.48   629.7 2400.69     704 2413.63   719.9 2417.88
   733.5 2419.57  745.152423.366  764.632427.709   814.7 2440.88   850.2 2448.74
#Mann= 6 ,-1 , 0
       0      .1       0     387    .045       0   396.9      .1       0
  436.18      .1       0  745.15     .05       0  764.63      .1       0
Bank Sta=387,396.9
XS Rating Curve= 0 ,0
Exp/Cntr=0.3,0.1

Type RM Length L Ch R = 1 ,6855    ,170.3,172,172.1
XS GIS Cut Line= 2
2425554.73315289557732.0236591712425131.72131557556959.938180929
#Sta/Elev= 30
       0 2581.91    15.3 2574.76    44.2 2563.75    94.3 2540.52   161.3  2506.2
   221.7 2473.26     257 2450.54   334.6 2403.81   368.3  2379.4     380 2368.49
   389.3  2365.5   406.6 2365.18   415.4 2361.85   420.9 2361.44   426.82361.881
     444  2363.8   494.9 2362.46   521.5  2366.1     538 2369.46  559.222375.303
   574.5 2381.55   585.4  2382.8     601 2390.51  618.012395.958   658.4 2406.76
   754.4 2425.61   772.4 2430.04   790.6 2431.83   822.5 2438.21   880.4 2451.46
#Mann= 5 ,-1 , 0
       0      .1       0   415.4    .045       0   426.8      .1       0
  559.22      .1       0  618.01     .05       0
Bank Sta=415.4,426.8
XS Rating Curve= 0 ,0
Exp/Cntr=0.3,0.1

Type RM Length L Ch R = 1 ,6683    ,169.6,169.5,169.7
XS GIS Cut Line= 2
2425671.23286536557639.9880140192425265.37153578556869.550007009
#Sta/Elev= 30
       0 2548.59   164.3 2468.38   227.6 2432.78   254.9 2416.08   322.5 2378.99
   337.9  2368.1   345.1  2361.3   349.8  2359.9     3702359.835   408.9 2359.65
   434.12361.025     4462358.605   453.3  2357.3   460.92358.687   503.4 2372.44
   515.5 2377.84     526 2378.78   530.3 2380.61   538.5 2385.77   553.1 2391.39
  640.332410.651   696.1 2420.48     705 2422.68   715.8 2423.58   722.8 2425.92
   733.9 2427.78   793.8  2441.2  846.552450.072   856.1 2452.55   870.8 2457.65
#Mann= 7 ,-1 , 0
       0      .1       0     370     .05       0   434.1      .1       0
     446    .045       0   460.9      .1       0  640.33     .05       0
  846.55      .1       0
#XS Ineff= 2 , 0
          385.51 2366.16
Permanent Ineff=
       F       F
Bank Sta=446,460.9
XS Rating Curve= 0 ,0
Exp/Cntr=0.3,0.1

Type RM Length L Ch R = 1 ,6513    ,149.9,148.8,147.4
XS GIS Cut Line= 2
2425813.48102103557542.1324894862425420.02867041556817.904067319
#Sta/Elev= 30
       0 2523.69    30.1 2513.21    59.6 2501.48    83.2 2490.88   126.9 2469.57
   233.6 2410.43   292.6 2378.97   301.4 2373.48   313.5 2364.42   318.1 2361.98
   340.8 2355.54   386.4 2356.02   397.82354.442   404.6  2353.5   410.6 2354.51
   436.4 2366.46   459.2 2374.79   463.7 2375.79   472.8 2375.98   481.9 2379.76
   503.9 2385.44   513.8 2388.82   527.5 2390.53   563.7 2397.64   613.9 2408.73
  667.282417.964   691.3 2421.96   743.8 2433.07     796 2441.25   824.2 2448.02
#Mann= 5 ,-1 , 0
       0      .1       0   397.8    .045       0   410.6      .1       0
   563.7     .05       0  667.28      .1       0
Bank Sta=397.8,410.6
XS Rating Curve= 0 ,0
Exp/Cntr=0.3,0.1

Type RM Length L Ch R = 1 ,6364    ,132.7,131,129.2
XS GIS Cut Line= 2
     2425984.735      557466.594      2425522.05       556782.31
#Sta/Elev= 30
       0 2487.23    22.4 2485.86    79.6 2478.97   109.9 2471.84  137.442463.162
     169 2452.24  209.862433.445   265.4 2405.95   334.5 2364.45   340.3 2360.25
     346 2354.58   348.9 2352.73   354.7 2352.06   395.9  2352.5   401.22351.166
   405.5 2349.51     408 2349.36   416.22350.661   450.9 2360.74   464.1 2365.49
   472.8 2367.34   484.3 2371.54   497.3 2372.23   504.7  2375.1   513.1 2377.32
   579.3 2390.35   622.8 2401.43   726.3 2419.61   769.5 2428.04     826  2441.2
#Mann= 5 ,-1 , 0
       0     .05       0  137.44      .1       0  209.86     .05       0
   401.2    .045       0   416.2     .05       0
Bank Sta=401.2,416.2
XS Rating Curve= 0 ,0
Exp/Cntr=0.3,0.1

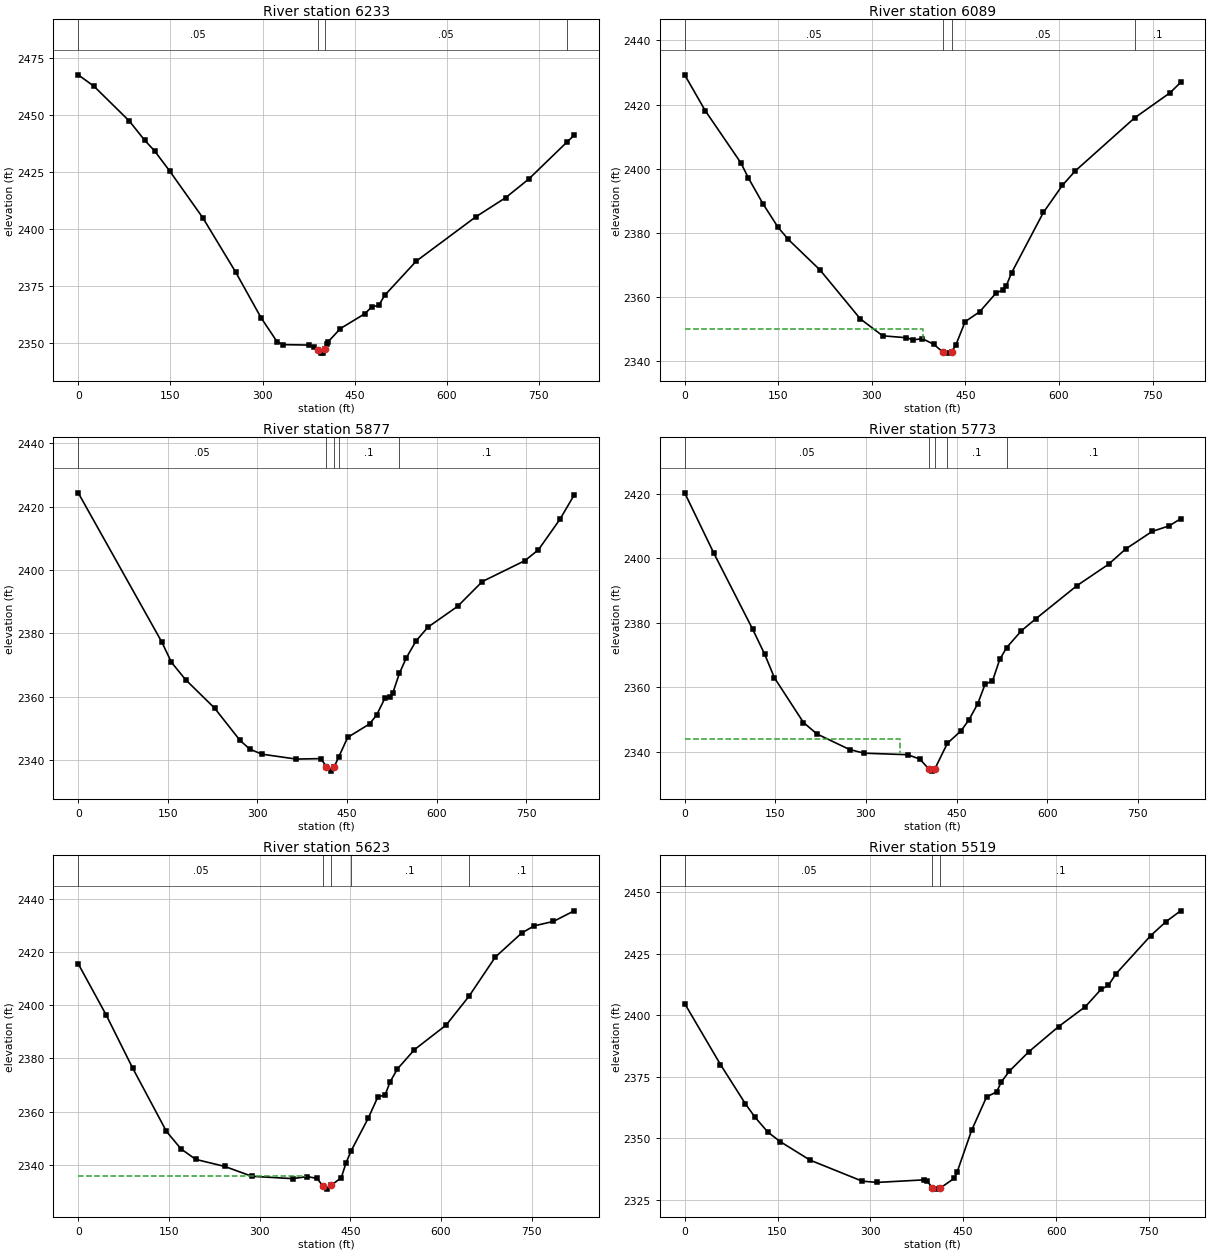
Type RM Length L Ch R = 1 ,6233    ,141,144,146.7
XS GIS Cut Line= 3
2425990.38814588  557403.43889342425917.26571759557111.787431437
     2425577.714      556735.848
#Sta/Elev= 30
       0 2467.73    25.6 2462.72    83.3  2447.4   108.1    2439   124.3 2434.31
   149.3 2425.32   202.9  2404.9   256.4 2381.01   297.7 2360.97   323.8 2350.43
   333.4 2349.19   375.9    2349   383.1 2348.34   390.12346.776   395.7 2345.46
   398.5 2345.59   401.4 2347.18   404.2 2349.42     407  2350.5   426.9 2356.27
   466.5 2362.76   477.8 2365.74   489.2 2366.49   499.2 2370.95   550.1 2385.84
   647.1 2405.32   695.9 2413.77   733.4 2421.94  795.812438.242   807.3 2441.15
#Mann= 4 ,-1 , 0
       0     .05       0   390.1    .045       0   401.4     .05       0
  795.81      .1       0
Bank Sta=390.1,401.4
XS Rating Curve= 0 ,0
Exp/Cntr=0.3,0.1

Type RM Length L Ch R = 1 ,6089    ,209.2,212.6,216
XS GIS Cut Line= 3
     2426164.008      557317.0272425938.74692567556905.691925672
2425724.97058207556659.511095357
#Sta/Elev= 30
       0 2429.27      33 2418.06    90.1 2401.78   101.8 2397.18   125.4 2389.03
   149.6 2381.68   166.2 2377.85   217.1 2368.29   281.6 2353.05   317.4 2347.77
   355.2 2347.17   366.1 2346.51   381.2 2346.86   399.4  2345.1   413.42342.766
   422.3 2342.36   428.12342.833   434.8 2344.98   449.6 2352.19     473 2355.29
   499.5 2361.21   509.8 2361.98   515.4 2363.31     524 2367.43     575 2386.28
   605.4 2394.74     626 2399.24  721.332415.835   777.9 2423.64     795 2426.89
#Mann= 4 ,-1 , 0
       0     .05       0   413.4    .045       0   428.1     .05       0
  721.33      .1       0
#XS Ineff= 2 , 0
          381.28    2350
Permanent Ineff=
       F       F
Bank Sta=413.4,428.1
XS Rating Curve= 0 ,0
Exp/Cntr=0.3,0.1

Type RM Length L Ch R = 1 ,5877    ,102.3,103.8,105.9
XS GIS Cut Line= 3
     2426247.747      557279.0822426148.45832258556828.804482476
 2425977.6818934556501.808429176
#Sta/Elev= 30
       0 2424.35   139.7  2377.3   156.1  2370.8   179.7 2365.34   228.2 2356.37
   270.8 2346.16   287.2 2343.39   307.6 2341.81     365 2340.26   405.9 2340.41
  415.34 2337.92   422.3 2336.46   428.62337.904  435.89 2340.89     451 2347.12
   487.7 2351.38   499.6 2354.24   513.1 2359.42   522.2 2359.88   526.7 2361.24
  537.52 2367.35   549.2 2372.27   565.4 2377.57   585.3 2381.93     635  2388.5
   676.3 2396.33   747.8 2402.95   770.3 2406.39   806.4 2416.03     830 2423.67
#Mann= 5 ,-1 , 0
       0     .05       0  415.34    .045       0   428.6     .05       0
  435.89      .1       0  537.52      .1       0
Bank Sta=415.34,428.6
XS Rating Curve= 0 ,0
Exp/Cntr=0.3,0.1

Type RM Length L Ch R = 1 ,5773    ,150,150,148.9
XS GIS Cut Line= 3
     2426290.972      557270.738     2426259.977      556860.717
      2426238.67      556451.675
#Sta/Elev= 30
       0 2420.34    48.2 2401.62   112.4 2378.04   132.5  2370.2   148.5 2362.92
   196.6 2349.03     219 2345.47   272.9 2340.65   296.9 2339.51   369.1 2339.04
   389.2 2337.68   403.72334.684   409.2 2333.94  414.35 2334.75  434.812342.586
   457.3 2346.44   470.1 2349.75     485 2354.83   497.3 2360.99   509.4  2361.9
   521.4  2368.6  532.852372.305   557.4 2377.54   581.4 2381.28   649.5 2391.56
   701.6 2398.17   729.6 2402.86   773.7 2408.35   801.7 2410.08   820.8 2412.27
#Mann= 5 ,-1 , 0
       0     .05       0   403.7    .045       0  414.35     .05       0
  434.81      .1       0  532.85      .1       0
#XS Ineff= 2 , 0
           356.6 2343.76
Permanent Ineff=
       F       F
Bank Sta=403.7,414.35
XS Rating Curve= 0 ,0
Exp/Cntr=0.3,0.1

Type RM Length L Ch R = 1 ,5623    ,104.4,104.4,104.7
XS GIS Cut Line= 3
      2426443.66      557264.134     2426409.076      556854.597
     2426355.853      556448.789
#Sta/Elev= 30
       0 2415.51      46 2396.39    89.8 2376.43     146  2352.5   170.1 2345.94
   194.2 2342.02   242.3 2339.36   287.1 2335.66   354.7 2334.77   378.8 2335.55
   394.9 2334.85   404.4 2332.14     411 2330.83   418.3 2332.23   435.1 2335.12
   443.2 2340.82  451.352345.193   479.5 2357.38   495.6 2365.47   507.7 2366.24
   515.8  2371.1   527.9 2375.97   556.1 2383.24   608.6 2392.49  646.462403.336
   689.9 2418.04   733.6 2427.09   754.1 2429.77   786.1 2431.44   820.3 2435.42
#Mann= 5 ,-1 , 0
       0     .05       0   404.4    .045       0   418.3     .05       0
  451.35      .1       0  646.46      .1       0
#XS Ineff= 2 , 0
          375.76 2335.68
Permanent Ineff=
       F       F
Bank Sta=404.4,418.3
XS Rating Curve= 0 ,0
Exp/Cntr=0.3,0.1

Type RM Length L Ch R = 1 ,5519    ,115.5,115,114.2
XS GIS Cut Line= 2
2426550.33001354557244.2168358872426474.46838612556446.586010354
#Sta/Elev= 30
       0 2404.77    57.8 2379.96      98    2364   113.5 2358.55   134.2 2352.48
   154.3 2348.58   202.5 2341.04   286.8 2332.48   310.9 2331.96   387.3 2333.01
   391.3 2332.55   400.22329.858     407 2329.23   413.22329.718   435.5 2333.64
   440.1 2336.16   463.6 2353.19   487.7 2366.77   503.8 2368.81   511.8 2372.92
   524.4 2377.23     556 2385.17   604.2 2395.43   647.5 2403.56   672.5 2410.52
   684.6  2412.2   696.6 2416.83   752.9 2432.44   777.6 2438.13   801.2 2442.53
#Mann= 3 ,-1 , 0
       0     .05       0   400.2    .045       0   413.2      .1       0
Bank Sta=400.2,413.2
XS Rating Curve= 0 ,0
Exp/Cntr(USF)=0,0
Exp/Cntr=0.3,0.1

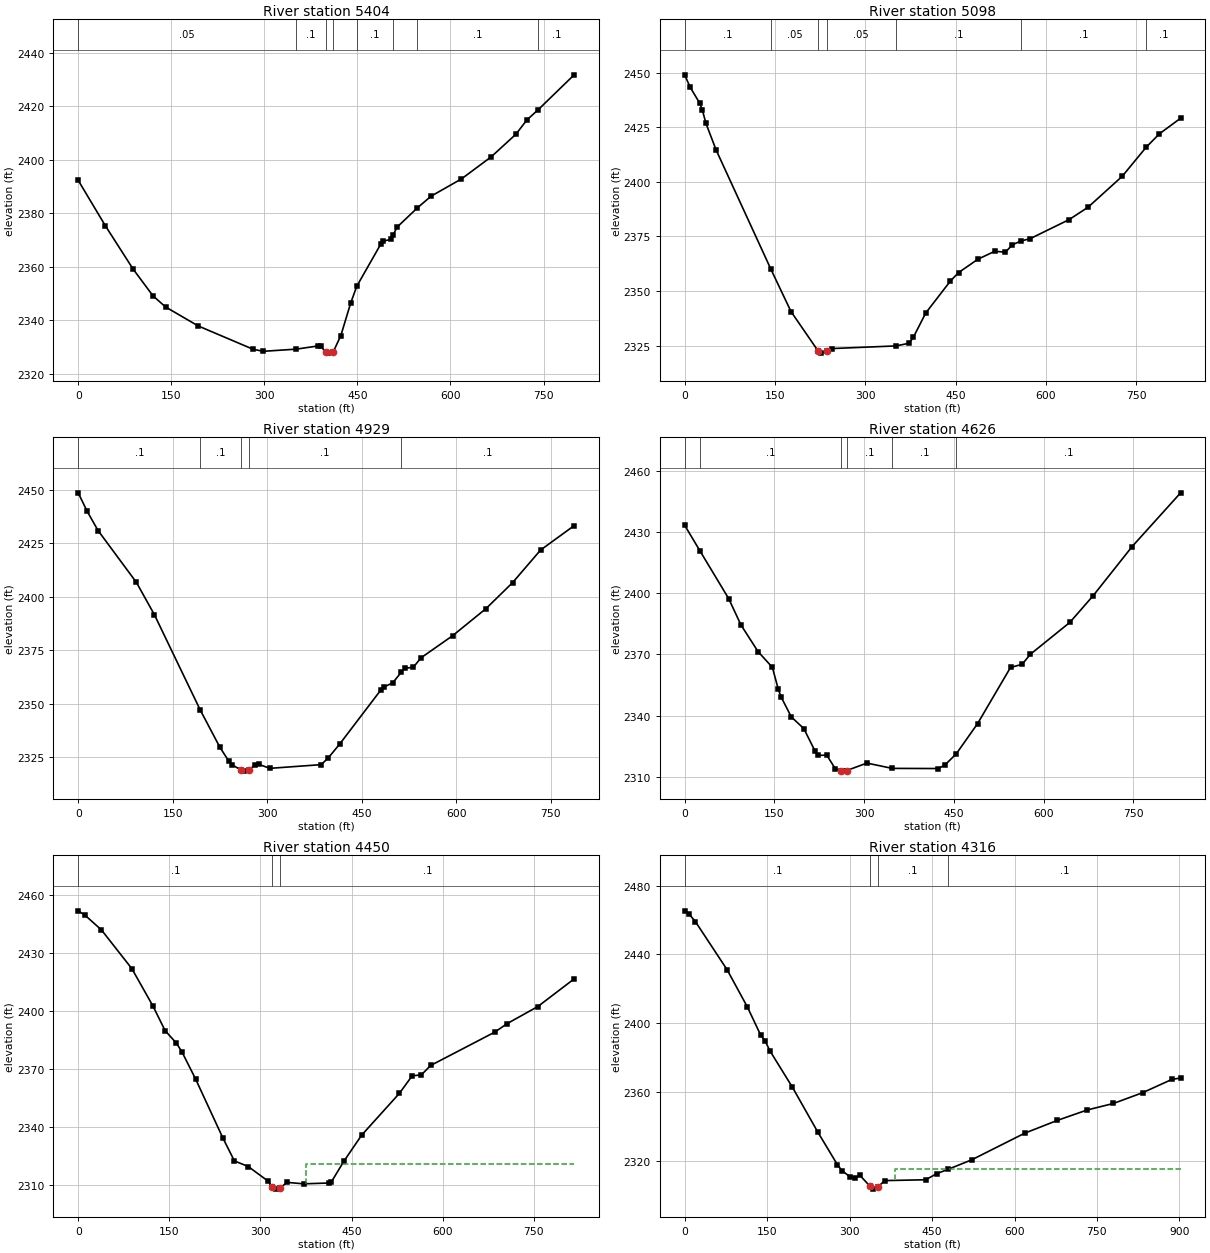
Type RM Length L Ch R = 1 ,5404    ,307.9,305.7,297.6
XS GIS Cut Line= 2
2426680.08048729557226.0379716962426570.66987468556434.302993149
#Sta/Elev= 30
       0 2392.35    43.8 2375.36    88.2 2359.28   120.5  2349.2   140.7 2345.05
   193.2 2337.96     282 2329.21   298.2 2328.46  351.51 2329.27     387 2330.48
     391  2330.3   398.92328.133   403.2 2327.78     411 2328.24   423.3 2334.36
   439.3 2346.62  449.052352.817   487.9 2368.63     492 2369.69   504.1 2370.27
  507.442371.911   513.8 2374.84  546.592382.063   568.7 2386.44   617.7 2392.89
   665.6 2401.14   705.4 2409.58   723.1 2414.91  741.672418.828   799.3 2431.79
#Mann= 8 ,-1 , 0
       0     .05       0  351.51      .1       0   398.9    .045       0
     411      .1       0  449.05      .1       0  507.44      .1       0
  546.59      .1       0  741.67      .1       0
Bank Sta=398.9,411
XS Rating Curve= 0 ,0
Exp/Cntr(USF)=0,0
Exp/Cntr=0.3,0.1

Type RM Length L Ch R = 1 ,5098    ,169.9,169.4,168.6
XS GIS Cut Line= 2
2426982.45163488557156.4130363962426582.60557787556436.292277014
#Sta/Elev= 30
       0 2448.96     8.9 2443.37    24.9 2436.01    29.5 2432.71    35.4 2426.68
    52.3 2414.49  142.822360.168   176.6 2340.55   221.6 2322.52   226.2 2321.52
   235.6 2322.46   244.5 2323.61  350.672324.823   372.6 2326.02   379.6 2328.68
   400.4  2339.9   441.3 2354.52   454.9  2358.4   486.9  2364.5   514.9 2368.15
   532.7 2367.76   544.3 2371.15  558.522372.863   573.9 2373.94   638.4 2382.65
   669.9 2388.31   726.7 2402.49  766.372415.773   788.4 2421.93   823.7  2429.1
#Mann= 7 ,-1 , 0
       0      .1       0  142.82     .05       0   221.6    .045       0
   235.6     .05       0  350.67      .1       0  558.52      .1       0
  766.37      .1       0
Bank Sta=221.6,235.6
XS Rating Curve= 0 ,0
Exp/Cntr(USF)=0,0
Exp/Cntr=0.3,0.1

Type RM Length L Ch R = 1 ,4929    ,303.2,302.4,303.2
XS GIS Cut Line= 3
2427145.35188032557076.8416817692426862.43150831556628.147654284
2426827.06646181556373.961382556
#Sta/Elev= 30
       0 2448.45    14.1 2439.87    31.5 2430.84    92.4  2406.6   120.8 2391.59
  193.882346.891   224.8 2329.65     239 2323.13   243.7 2321.48   258.8 2318.96
   262.6 2318.47   270.9 2319.05   279.9 2321.15   286.3 2321.68   304.1 2319.77
   385.6  2321.5   396.9 2324.66   414.9 2331.08   480.1 2356.29   484.9 2357.74
   499.1 2359.68  512.682364.651   518.7 2366.52   531.9 2366.99     544 2371.38
   594.1 2381.69   647.3  2394.4   689.4 2406.51   733.8 2421.72   787.1 2433.12
#Mann= 5 ,-1 , 0
       0      .1       0  193.88      .1       0   258.8    .045       0
   270.9      .1       0  512.68      .1       0
Bank Sta=258.8,270.9
XS Rating Curve= 0 ,0
Exp/Cntr(USF)=0,0
Exp/Cntr=0.3,0.1

Type RM Length L Ch R = 1 ,4626    ,175.5,176.6,178.2
XS GIS Cut Line= 3
 2427415.0103599556977.3774884842427123.24872626556530.893776405
2426919.89970888556316.493181992
#Sta/Elev= 30
       0 2433.44   25.812420.728    73.5 2397.46      94 2384.54   122.6 2371.44
   146.6 2363.66   156.1 2353.29   160.9 2349.29   178.2 2339.35   199.1 2333.62
     218  2322.5     223 2320.44   237.4  2320.6   251.7 2313.92     261 2313.02
     266 2312.73   270.8 2313.02   304.6 2316.68  346.912314.075   423.7    2314
   434.7 2315.66  453.95 2321.24   489.6 2336.08   544.6 2363.64     564 2365.16
   577.7 2370.08   643.9 2385.79   682.9 2398.93   747.9 2423.01   828.9 2449.37
#Mann= 6 ,-1 , 0
       0      .1       0   25.81      .1       0     261    .045       0
   270.8      .1       0  346.91      .1       0  453.95      .1       0
Bank Sta=261,270.8
XS Rating Curve= 0 ,0
Exp/Cntr(USF)=0,0
Exp/Cntr=0.3,0.1

Type RM Length L Ch R = 1 ,4450    ,130.1,133.7,136.9
XS GIS Cut Line= 3
2427541.74449663556908.0737478432427332.82157469556527.096654898
2427037.87156725556284.816291642
#Sta/Elev= 30
       0  2451.8    11.2 2449.52    38.1 2441.97    88.3 2421.87   123.1 2402.47
     143 2389.79   161.4 2383.39   170.4 2378.99   193.2 2364.75     238 2334.29
     257 2322.37   279.8 2319.48   311.8 2312.07   319.62308.927   325.5 2307.77
   332.72308.602     344 2311.26   371.1 2310.51   412.1 2310.94   416.7 2311.54
   437.5 2322.34   466.5 2335.71   528.7 2357.38   549.4 2366.34   564.9 2366.96
     580 2371.76   685.4    2389   706.1 2393.46   756.5 2402.28   816.2 2416.58
#Mann= 3 ,-1 , 0
       0      .1       0   319.6    .045       0   332.7      .1       0
#XS Ineff= 2 , 0
                          374.77         2320.93
Permanent Ineff=
       F       F
Bank Sta=319.6,332.7
XS Rating Curve= 0 ,0
Exp/Cntr(USF)=0,0
Exp/Cntr=0.3,0.1

Type RM Length L Ch R = 1 ,4316    ,90.9,91.2,91.6
XS GIS Cut Line= 3
2427585.20464618556917.6989725132427474.68887587556427.008952308
2427176.29629601556161.771103549
#Sta/Elev= 30
       0 2465.33     7.7 2463.55    19.5 2459.08    77.2 2431.12     114 2409.56
   138.4 2393.07   146.6 2389.66   154.8 2384.19   195.8 2363.01   242.1  2336.9
   277.9 2317.92     286 2314.49   301.3  2310.8   310.6 2310.34   318.8 2311.72
   337.22305.419   343.4 2303.75   352.22305.208   363.9  2308.7   438.5 2309.19
   458.6 2312.76  479.392315.268   522.6 2320.83   618.4  2336.2   677.8 2343.65
   732.2  2349.7   779.9 2353.48     833 2359.73   886.5 2367.48   902.2 2368.27
#Mann= 4 ,-1 , 0
       0      .1       0   337.2    .045       0   352.2      .1       0
  479.39      .1       0
#XS Ineff= 2 , 0
                          382.54         2315.39
Permanent Ineff=
       F       F
Bank Sta=337.2,352.2
XS Rating Curve= 0 ,0
Exp/Cntr(USF)=0,0
Exp/Cntr=0.5,0.3

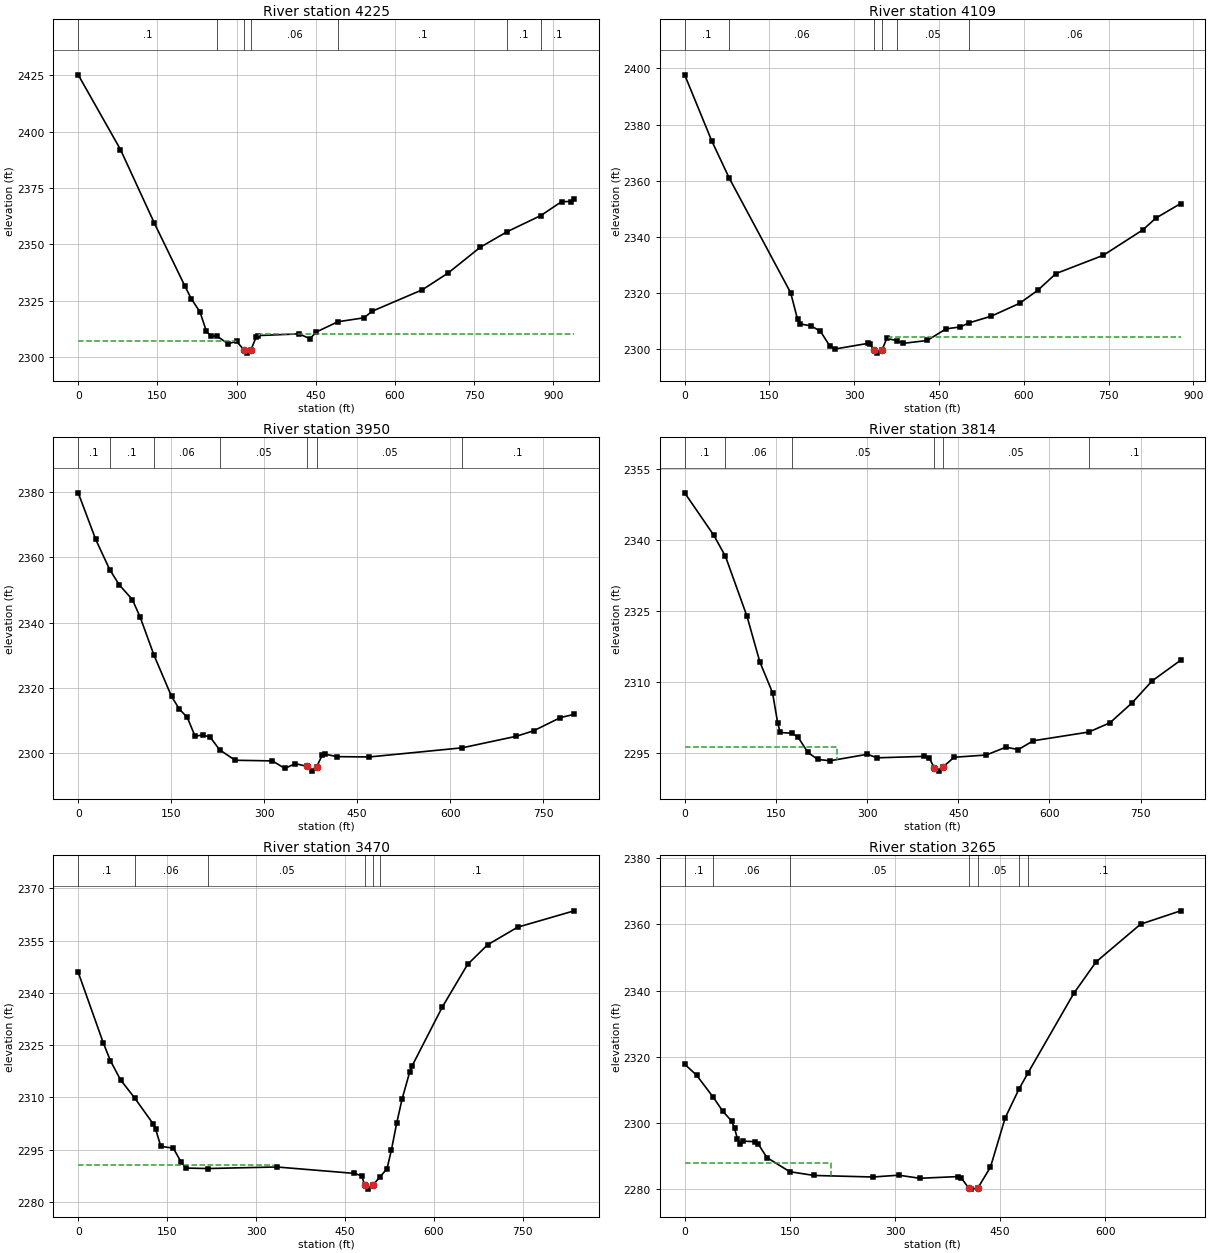
Type RM Length L Ch R = 1 ,4225    ,116.5,115.4,114.1
XS GIS Cut Line= 3
2427664.77600081556884.5442414182427543.20865346556298.810658741
2427269.12954308556095.461641359
#Sta/Elev= 30
       0 2425.19    80.1    2392   144.3 2359.32   202.4 2331.27   214.3 2325.72
   230.7 2319.93   242.9 2311.27   251.1 2309.31  263.042309.143   283.8 2305.83
   300.1 2306.83   314.7 2302.92   320.5 2301.64  326.76 2302.91   336.9 2308.61
   340.9 2309.44   418.3 2310.18     439 2308.04   451.2 2311.04   492.1 2315.58
   541.1 2317.31   557.4 2320.29     652 2329.78   700.6 2337.18   761.6 2348.63
  812.922355.595  876.382362.714     916 2368.93     934 2368.93   939.5 2370.12
#Mann= 7 ,-1 , 0
       0      .1       0  263.04     .06       0   314.7    .045       0
  326.76     .06       0   492.1      .1       0  812.92      .1       0
  876.38      .1       0
#XS Ineff= 2 , 0
       0  298.17    2307  341.93       0    2310
Permanent Ineff=
       F       F
Bank Sta=314.7,326.76
XS Rating Curve= 0 ,0
Exp/Cntr(USF)=0,0
Exp/Cntr=0.5,0.3

Type RM Length L Ch R = 1 ,4109    ,157.1,159.7,162.5
XS GIS Cut Line= 3
2427746.55767085556882.3339260122427746.55767085 556654.67143916
2427550.83850698556035.105683124
#Sta/Elev= 30
       0 2397.74    47.7 2374.25   78.962360.828   187.6 2319.91   199.6 2310.53
   203.6 2308.85   223.6 2308.13   240.2  2306.2     257 2300.86   265.4 2299.86
   324.1 2301.87   328.3 2301.61  335.05 2299.43   340.9  2298.4     3492299.526
   357.7 2303.67     3752302.867     387  2301.9     429 2302.91   462.5 2307.07
   487.9 2307.75  502.65 2309.17   542.5  2311.6   592.5 2316.17   624.9 2320.87
   656.8 2326.79   740.8 2333.34   810.7 2342.42   833.7 2346.61   877.4 2351.79
#Mann= 6 ,-1 , 0
       0      .1       0   78.96     .06       0  335.05    .045       0
     349     .06       0     375     .05       0  502.65     .06       0
#XS Ineff= 2 , 0
                          361.91         2304.01
Permanent Ineff=
       F       F
Bank Sta=335.05,349
XS Rating Curve= 0 ,0
Exp/Cntr(USF)=0,0
Exp/Cntr=0.5,0.3

Type RM Length L Ch R = 1 ,3950    ,136.8,135.4,134
XS GIS Cut Line= 3
2427822.99342297 556901.462007282427884.83536191556716.154863319
2427837.42346947556113.614738375
#Sta/Elev= 30
       0 2379.75    28.2 2365.48   50.782356.264    66.2 2351.58    87.3 2347.08
    99.9  2341.7  122.26 2330.03   150.5 2317.42   163.2 2313.51   175.8 2311.03
   188.5 2305.24   200.8 2305.64   212.9 2304.94  228.012301.099     253 2297.89
   313.2 2297.69   333.2 2295.39     350 2296.85   369.3 2296.02   377.4 2294.56
   384.3  2295.8   393.4  2299.4   397.4  2299.8     417 2298.99   469.6  2298.9
  619.242301.697   706.3 2305.22   734.4  2306.9   777.7 2310.95   799.8 2311.94
#Mann= 7 ,-1 , 0
       0      .1       0   50.78      .1       0  122.26     .06       0
  228.01     .05       0   369.3    .045       0   384.3     .05       0
  619.24      .1       0
Bank Sta=369.3,384.3
XS Rating Curve= 0 ,0
Exp/Cntr=0.3,0.1

Type RM Length L Ch R = 1 ,3814    ,339,344.7,350.8
XS GIS Cut Line= 3
2427994.11299635556924.3299187322428049.37088151556751.925317038
2427930.01384957556128.616372454
#Sta/Elev= 30
       0 2349.94    47.9 2340.97    67.12336.516   102.5 2323.85   123.6 2314.24
   144.5 2307.72   152.9 2301.39   157.1 2299.32  176.172299.167   186.4 2298.35
   202.7  2295.1     219 2293.62   239.3 2293.35   300.4 2294.72   316.7 2293.97
   394.1 2294.28   402.2 2293.94   410.42291.906   418.5 2291.16   425.22292.058
   443.1 2294.09   495.9 2294.56   528.4 2296.22   548.8 2295.71   573.2 2297.57
  664.622299.414   699.5 2301.37   736.1 2305.61   768.7  2310.2   815.7 2314.58
#Mann= 6 ,-1 , 0
       0      .1       0    67.1     .06       0  176.17     .05       0
   410.4    .045       0   425.2     .05       0  664.62      .1       0
#XS Ineff= 2 , 0
          250.18 2296.24
Permanent Ineff=
       F       F
Bank Sta=410.4,425.2
XS Rating Curve= 0 ,0
Exp/Cntr(USF)=0,0
Exp/Cntr=0.3,0.1

Type RM Length L Ch R = 1 ,3470    ,204.9,204.6,204.1
XS GIS Cut Line= 2
2428109.04939748556942.0124419832428387.54913868556152.929841923
#Sta/Elev= 30
       0 2345.91    42.5 2325.56    54.4 2320.51    71.4 2315.04   95.222309.836
   126.5 2302.39   130.8  2300.8   139.3 2295.95   160.5 2295.41   173.2 2291.55
   181.7  2289.7  218.732289.573     335 2290.02   465.9 2288.18   478.3 2287.48
  483.58 2284.75   489.4 2283.66   497.1 2284.76   509.5 2287.26     521  2289.5
   528.4 2294.85   537.4 2302.62   546.4 2309.48   559.2 2317.22   562.9 2318.88
   614.3 2335.93   656.9 2348.16   690.6 2353.79   741.4 2358.86   836.8 2363.56
#Mann= 6 ,-1 , 0
       0      .1       0   95.22     .06       0  218.73     .05       0
  483.58    .045       0   497.1     .05       0   509.5      .1       0
#XS Ineff= 2 , 0
          327.84 2290.55
Permanent Ineff=
       F       F
Bank Sta=483.58,497.1
XS Rating Curve= 0 ,0
Exp/Cntr(USF)=0,0
Exp/Cntr=0.3,0.1

Type RM Length L Ch R = 1 ,3265    ,230.9,230.8,229.3
XS GIS Cut Line= 2
2428334.50156893556946.4330727952428548.90216334556272.286873865
#Sta/Elev= 30
       0 2317.81    16.9 2314.51   40.852307.815    54.3 2303.62    66.9 2300.67
    71.1 2298.48    75.3 2295.27    79.5 2293.78    83.8 2294.57   100.5 2294.42
   104.7 2293.79   117.3 2289.62   149.8 2285.36   184.4 2284.22   268.6 2283.75
   305.2  2284.3   335.3 2283.37   390.1 2283.88   394.3 2283.53   405.3 2280.38
   408.5 2280.09   418.1 2280.39   436.2 2286.76   457.2 2301.62  476.652310.218
  489.462315.086     555 2339.19   586.8  2348.7   650.3 2360.09   707.4 2364.12
#Mann= 7 ,-1 , 0
       0      .1       0   40.85     .06       0   149.8     .05       0
   405.3    .045       0   418.1     .05       0  476.65      .1       0
  489.46      .1       0
#XS Ineff= 2 , 0
          208.76 2288.11
Permanent Ineff=
       F       F
Bank Sta=405.3,418.1
XS Rating Curve= 0 ,0
Exp/Cntr(USF)=0,0
Exp/Cntr=0.3,0.1

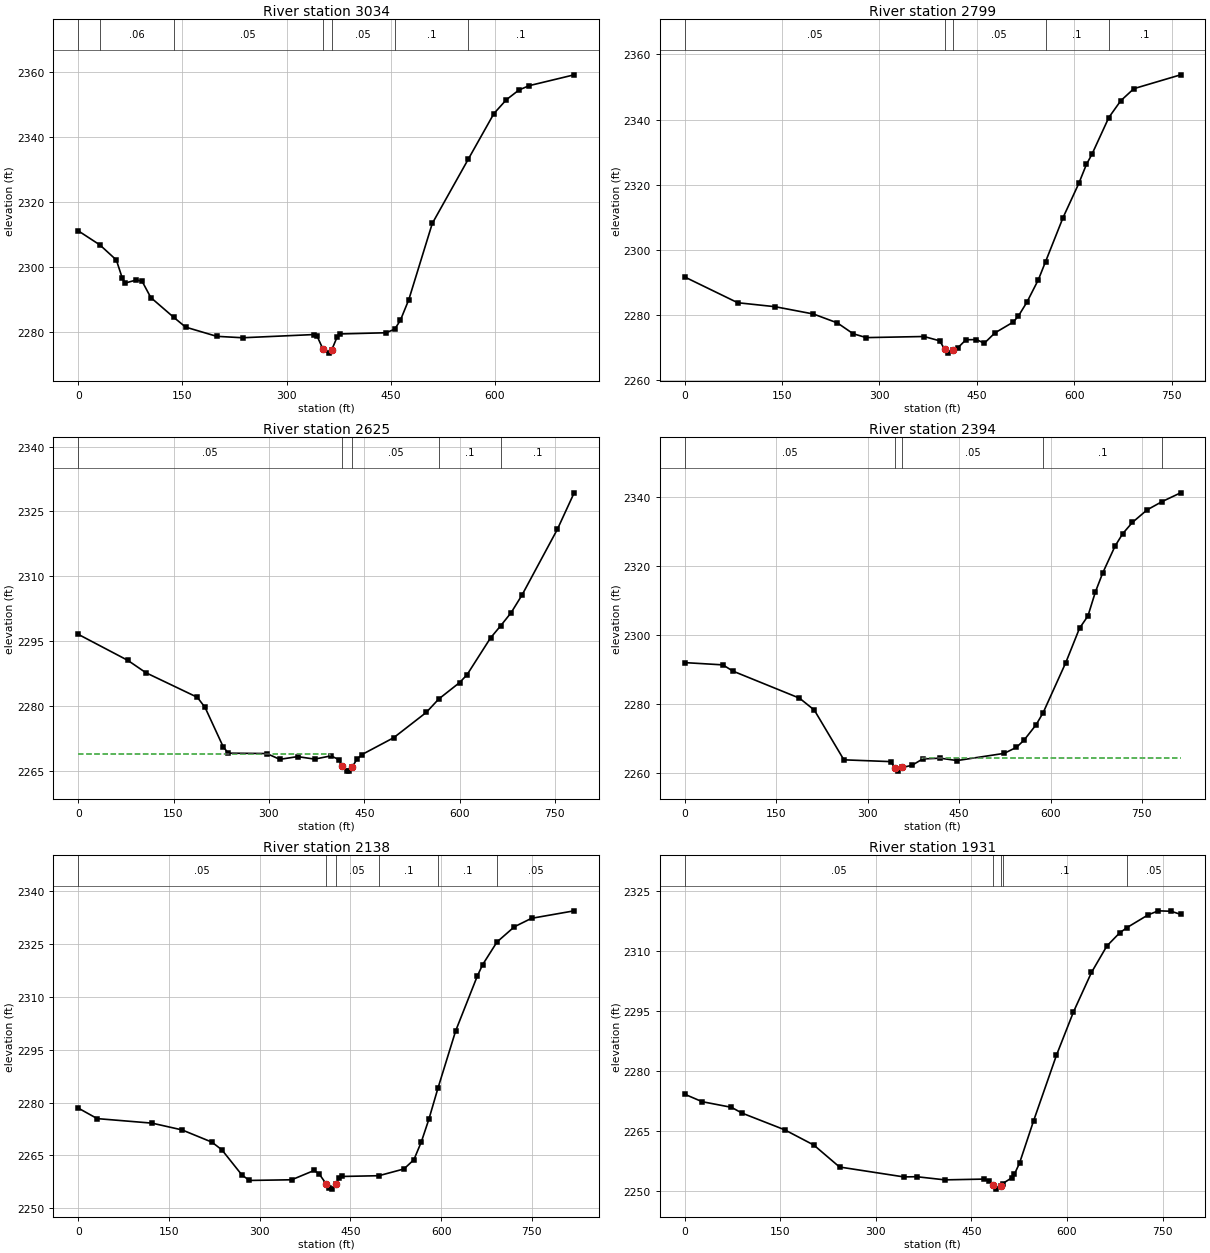
Type RM Length L Ch R = 1 ,3034    ,238.8,234.9,229.8
XS GIS Cut Line= 2
2428548.90216334 557003.901273362428725.72739585556312.072551179
#Sta/Elev= 30
       0 2311.05   31.262306.697    54.9 2302.07    63.2 2296.65    67.3 2294.95
    83.8 2295.93    92.1 2295.48   104.5 2290.52  137.34 2284.46   154.7 2281.41
   199.4 2278.58   236.9 2278.14   339.8 2279.13   343.9 2278.66   352.5 2274.62
   360.4 2273.41   365.1 2274.42   372.8 2278.39   376.9 2279.31     443 2279.68
  455.592280.757   463.8 2283.46     476 2289.86   509.8 2313.31  561.672333.104
   598.6 2347.14   616.4 2351.37   634.7 2354.39   649.4 2355.72   714.1 2359.05
#Mann= 7 ,-1 , 0
       0     .05       0   31.26     .06       0  137.34     .05       0
   352.5    .045       0   365.1     .05       0  455.59      .1       0
  561.67      .1       0
Bank Sta=352.5,365.1
XS Rating Curve= 0 ,0
Exp/Cntr(USF)=0,0
Exp/Cntr=0.3,0.1

Type RM Length L Ch R = 1 ,2799    ,174.7,174.8,174.7
XS GIS Cut Line= 2
2428929.07641323557083.4726279882428818.56064291556327.544759023
#Sta/Elev= 30
       0 2291.62    81.7  2283.7   139.3 2282.48   198.4 2280.23   235.3 2277.49
   259.5 2274.17   279.7 2272.98   368.7 2273.32   392.9 2271.99   400.3 2269.45
     405 2268.21   413.32269.279   421.2 2269.92   433.3 2272.32   449.5 2272.37
   461.6 2271.25   477.9 2274.42   506.2 2277.76   514.2 2279.64   527.3  2283.9
   544.9  2290.8  555.862296.286   582.9 2309.88   607.1 2320.35   618.9 2326.22
   627.4 2329.33  653.39 2340.63   671.8 2345.79     692  2349.5     764 2353.75
#Mann= 5 ,-1 , 0
       0     .05       0   400.3    .045       0   413.3     .05       0
  555.86      .1       0  653.39      .1       0
Bank Sta=400.3,413.3
XS Rating Curve= 0 ,0
Exp/Cntr(USF)=0,0
Exp/Cntr=0.3,0.1

Type RM Length L Ch R = 1 ,2625    ,228.8,230.1,230.2
XS GIS Cut Line= 2
2429103.69133033557068.0004201432428986.54461379556296.600343335
#Sta/Elev= 30
       0 2296.55    78.2  2290.5   106.5 2287.65   187.4 2281.96   199.6  2279.6
   227.9 2270.56     236 2269.02   296.7 2268.93   317.1 2267.59   345.2 2268.22
     372 2267.64   397.8  2268.4   409.9 2267.52   415.42266.022   422.1 2264.86
   426.1 2264.88   430.6 2265.73   438.3 2267.56   446.4  2268.7   496.3  2272.6
   547.5 2278.45  567.362281.587   600.1 2285.38   611.8 2287.21   648.6  2295.7
  664.882298.578     681 2301.55   698.2 2305.65   753.8 2320.87   780.2 2329.32
#Mann= 5 ,-1 , 0
       0     .05       0   415.4    .045       0   430.6     .05       0
  567.36      .1       0  664.88      .1       0
#XS Ineff= 2 , 0
          395.37 2268.94
Permanent Ineff=
       F       F
Bank Sta=415.4,430.6
XS Rating Curve= 0 ,0
Exp/Cntr(USF)=0,0
Exp/Cntr=0.3,0.1

Type RM Length L Ch R = 1 ,2394    ,257.1,256.7,255.6
XS GIS Cut Line= 2
2429309.25066312557056.9488431122429189.89363118556252.394035208
#Sta/Elev= 30
       0 2291.93    62.7 2291.27    79.1 2289.46   188.3 2281.61   212.6 2278.15
   261.1 2263.71   337.9 2263.19   344.8 2261.47     350 2260.43   357.1 2261.49
     373 2262.14   390.3 2263.96   418.8 2264.19   446.9  2263.5   523.9 2265.58
   544.1 2267.33   556.3 2269.36   576.5 2273.91     5882277.421     625  2291.9
   647.6 2301.91   661.4 2305.47   673.5 2312.38   685.6 2317.94   705.9 2325.75
   718.5 2329.37   734.2  2332.6   758.4 2336.26  783.062338.672   813.4 2341.21
#Mann= 5 ,-1 , 0
       0     .05       0   344.8    .045       0   357.1     .05       0
     588      .1       0  783.06     .05       0
#XS Ineff= 2 , 0
                          389.44         2264.29
Permanent Ineff=
       F       F
Bank Sta=344.8,357.1
XS Rating Curve= 0 ,0
Exp/Cntr(USF)=0,0
Exp/Cntr=0.3,0.1

Type RM Length L Ch R = 1 ,2138    ,206.1,207,207.7
XS GIS Cut Line= 3
2429594.38135054557017.1631657982429455.13147994556457.953367997
2429419.76643344556217.028988707
#Sta/Elev= 30
       0 2278.42    31.4 2275.42   122.1 2274.13   171.6 2272.21     221 2268.73
   237.5 2266.54   270.5 2259.41   282.9 2257.84   352.9 2258.03     390 2260.68
   398.3  2259.7   409.82256.867   414.7 2255.56   418.9 2255.37   425.42256.762
   431.2 2258.54   435.4 2258.97  496.932259.184   538.4  2261.1   554.9 2263.73
   567.3 2268.87   579.6 2275.21  594.772284.143     624  2300.4   659.6  2315.9
   668.5 2319.19   692.32325.652     721 2329.97   749.3 2332.37   819.8  2334.5
#Mann= 6 ,-1 , 0
       0     .05       0   409.8    .045       0   425.4     .05       0
  496.93      .1       0  594.77      .1       0   692.3     .05       0
Bank Sta=409.8,425.4
XS Rating Curve= 0 ,0
Exp/Cntr(USF)=0,0
Exp/Cntr=0.3,0.1

Type RM Length L Ch R = 1 ,1931    ,273.2,272.2,270.1
XS GIS Cut Line= 3
2429649.63923569556992.8496963282429707.10743626556802.762571384
2429631.95671244556228.080565738
#Sta/Elev= 30
       0 2274.17    27.4  2272.3    73.3 2270.89      90 2269.44   156.9 2265.26
   202.7 2261.43     243 2255.94   343.9 2253.46     364 2253.51   408.4 2252.72
   468.9 2252.91     477  2252.5   483.4 2251.47   489.1  2250.4   495.92251.156
  499.04 2251.79   513.3 2253.25   517.3 2254.11   525.4  2256.9   547.6 2267.56
   583.3  2283.9   610.1  2294.8   638.3 2304.66   662.5  2311.3   682.7  2314.6
  694.152315.912   727.1 2319.08   743.2  2320.1   763.4 2319.99   778.2 2319.21
#Mann= 5 ,-1 , 0
       0     .05       0   483.4    .045       0   495.9     .05       0
  499.04      .1       0  694.15     .05       0
Bank Sta=483.4,495.9
XS Rating Curve= 0 ,0
Exp/Cntr(USF)=0,0
Exp/Cntr=0.3,0.1