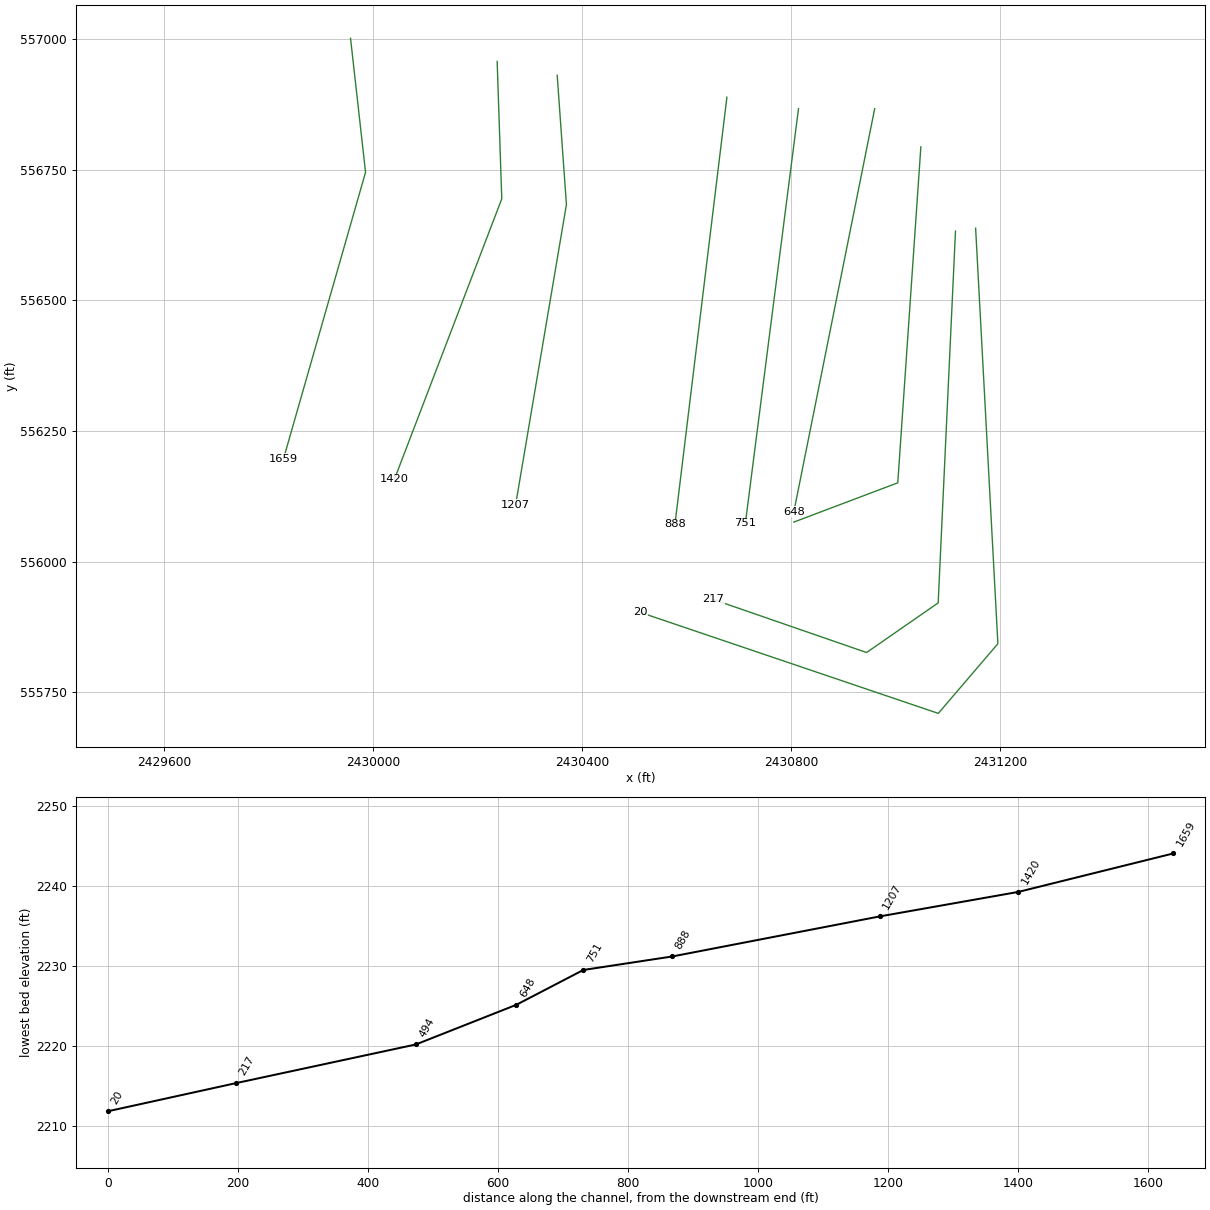
HEC-RAS study LONGRN1.prj: LONGRN1

--- LONGRN1.g01 (geometry) --- (continued)

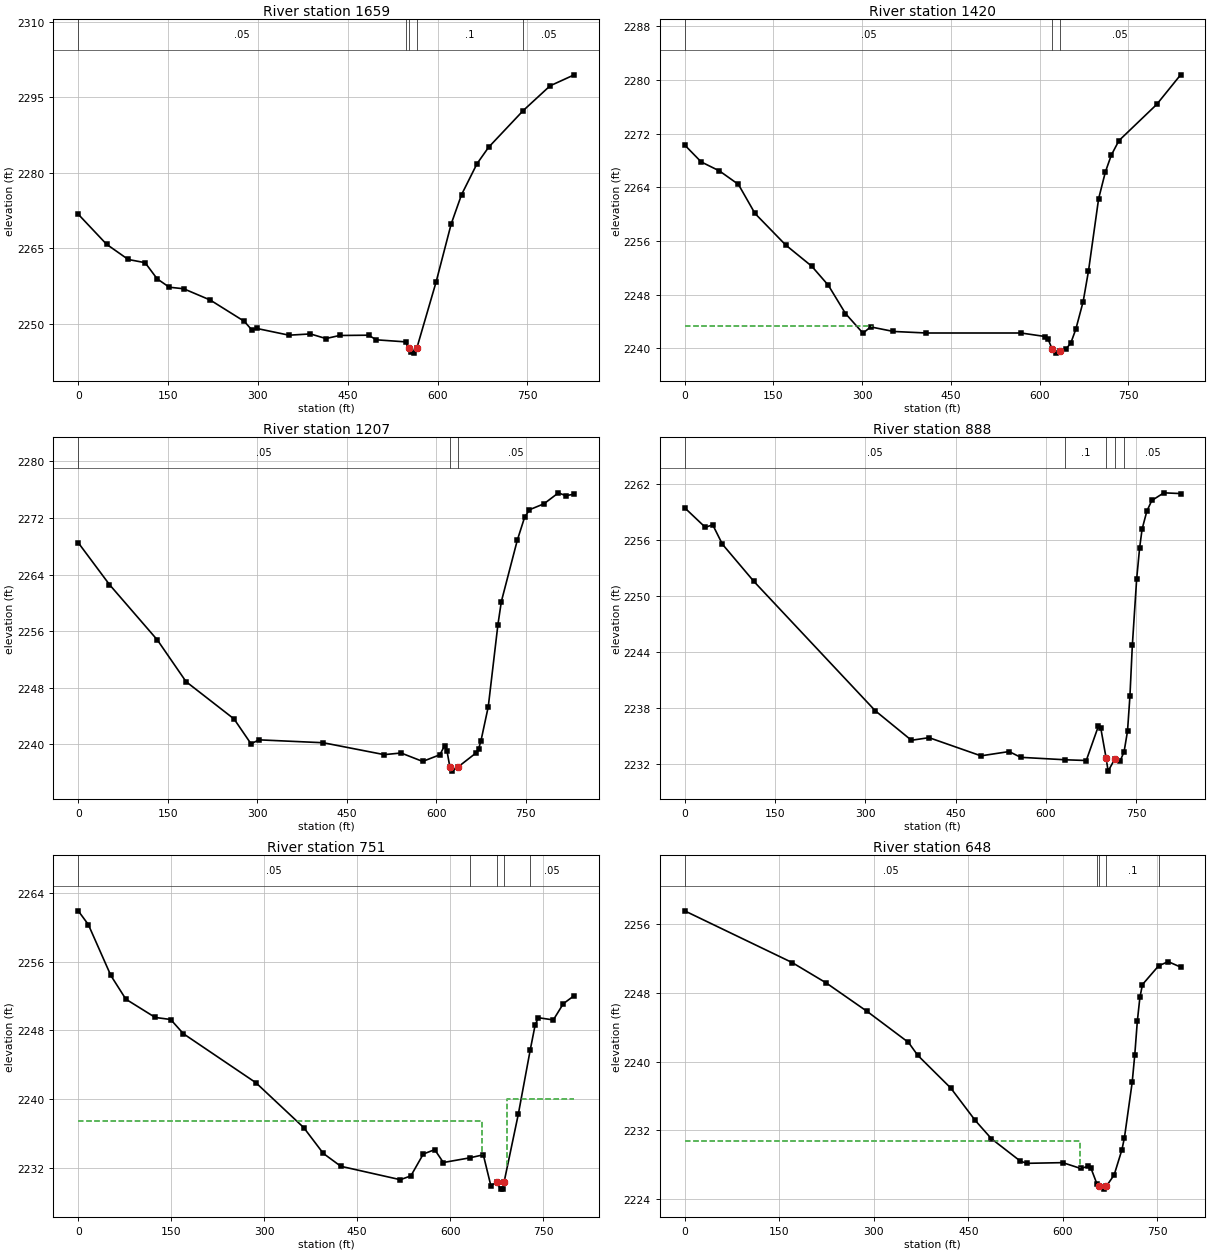
Type RM Length L Ch R = 1 ,1659    ,239.5,238.4,237.4
XS GIS Cut Line= 3
2429956.87307717557001.6909579532429985.60717746556745.294370819
2429828.67478361 556197.13615005
#Sta/Elev= 30
       0 2271.77    47.3 2265.79    83.5 2262.76   111.7 2262.12   131.8 2258.91
     152 2257.24   176.1 2256.93   220.4 2254.69   277.4 2250.44   289.8 2248.74
   298.2 2249.03     352 2247.69   387.8 2247.94   413.6 2247.02   436.3 2247.63
   484.8 2247.69   497.8 2246.77  546.572246.361   551.9 2245.11   555.9 2244.27
   560.2 2244.12   565.6  2245.2   597.7 2258.33   622.7  2269.8     640 2275.64
   665.9 2281.82   685.3  2285.1  743.152292.409   787.9 2297.32   828.2 2299.51
#Mann= 5 ,-1 , 0
       0     .05       0  546.57      .1       0   551.9    .045       0
   565.6      .1       0  743.15     .05       0
Bank Sta=551.9,565.6
XS Rating Curve= 0 ,0
Exp/Cntr(USF)=0,0
Exp/Cntr=0.3,0.1

Type RM Length L Ch R = 1 ,1420    ,211.2,213.2,215.4
XS GIS Cut Line= 3
2430237.58313378556957.484649827 2430246.4243954556694.457116474
2430040.86506261556157.350472736
#Sta/Elev= 30
       0 2270.33      28  2267.8    58.8 2266.46    90.9 2264.45   118.9 2260.12
   170.9 2255.41   214.9 2252.25   242.9 2249.41   271.9  2245.2   301.5 2242.27
   314.3 2243.21   352.9 2242.53   408.5  2242.3   568.6  2242.3   609.8 2241.77
   614.1 2241.44   621.3 2239.87   626.9  2239.3     6342239.642   644.1 2239.87
   652.6 2240.78   661.2 2242.87   673.6 2246.99   682.6 2251.55   699.7 2262.31
   711.1 2266.29   721.1  2268.8     734 2270.97   797.8 2276.36   838.3 2280.78
#Mann= 3 ,-1 , 0
       0     .05       0   621.3    .045       0     634     .05       0
#XS Ineff= 2 , 0
          316.29 2243.35
Permanent Ineff=
       F       F
Bank Sta=621.3,634
XS Rating Curve= 0 ,0
Exp/Cntr(USF)=0,0
Exp/Cntr=0.3,0.1

Type RM Length L Ch R = 1 ,1207    ,317.5,319.3,318.8
XS GIS Cut Line= 3
2430352.51953491556930.9608649512430370.20205816556683.405539442
2430272.94818028556108.723533797
#Sta/Elev= 30
       0 2268.51    52.4 2262.58   132.6 2254.76   180.7 2248.87   261.1  2243.6
   289.5 2240.09     303 2240.65   410.6 2240.24   512.6 2238.56     541 2238.79
   577.1  2237.6   605.9 2238.54     614 2239.85     618 2239.01   622.8 2236.76
   626.2 2236.23   636.1  2236.8   666.7 2238.81   670.8 2239.37   674.8 2240.53
     687 2245.33   703.2 2256.94   708.9 2260.18   735.7 2268.87   747.8 2272.07
     756 2273.16   780.3    2274   804.6 2275.55   816.8 2275.14     831 2275.37
#Mann= 3 ,-1 , 0
       0     .05       0   622.8    .045       0   636.1     .05       0
Bank Sta=622.8,636.1
XS Rating Curve= 0 ,0
Exp/Cntr(USF)=0,0
Exp/Cntr=0.3,0.1

Type RM Length L Ch R = 1 ,888     ,136.6,136.6,136.7
XS GIS Cut Line= 2
2430677.43589964556888.9648722312430577.97170635556071.148171889
#Sta/Elev= 30
       0 2259.47    34.5 2257.36    46.6 2257.65    62.7 2255.56   115.1 2251.56
   316.6 2237.69   376.7 2234.52     406  2234.8   492.2 2232.85   538.9 2233.31
   558.3 2232.69  632.382232.428   667.1 2232.35   687.2 2236.03   691.3 2235.79
     7002232.632   703.4 2231.21   714.42232.502   723.5 2232.31  729.962233.313
   735.6  2235.5   739.6 2239.24   743.6 2244.69   750.8 2251.84   755.7 2255.15
   759.8 2257.17   767.8 2259.12     776 2260.25     796 2261.07   823.8 2260.99
#Mann= 5 ,-1 , 0
       0     .05       0  632.38      .1       0     700    .045       0
   714.4      .1       0  729.96     .05       0
Bank Sta=700,714.4
XS Rating Curve= 0 ,0
Exp/Cntr(USF)=0,0
Exp/Cntr=0.5,0.3

Type RM Length L Ch R = 1 ,751     ,105.9,103,104.4
XS GIS Cut Line= 2
2430814.47545483556866.8617181672430712.80094614556073.358487295
#Sta/Elev= 30
       0 2261.94    16.3 2260.34    52.6 2254.41    76.8 2251.65   124.2 2249.52
   149.2 2249.28   169.5 2247.63   286.5 2241.92   363.7 2236.69   395.3 2233.68
   423.6 2232.18   519.5 2230.62   536.5 2231.06   556.6 2233.61     575 2234.12
   588.9 2232.62  631.452233.163   653.4 2233.52   665.5 2229.93   674.7  2230.3
   681.6 2229.52   685.7 2229.59  686.86 2230.33   709.9 2238.27  729.012245.716
   736.9 2248.61   742.1 2249.49   766.3 2249.23   782.4 2251.12     800 2252.06
#Mann= 5 ,-1 , 0
       0     .05       0  631.45      .1       0   674.7    .045       0
  686.86      .1       0  729.01     .05       0
#XS Ineff= 2 , 0
       0  650.89  2237.5   692.3       0    2240
Permanent Ineff=
       F       F
Bank Sta=674.7,686.86
XS Rating Curve= 0 ,0
Exp/Cntr(USF)=0,0
Exp/Cntr=0.5,0.3

Type RM Length L Ch R = 1 ,648     ,168.7,154.6,145.5
XS GIS Cut Line= 2
2430960.35627165556866.861718167 2430805.6341932556095.461641359
#Sta/Elev= 30
       0 2257.52   170.7  2251.5   224.5 2249.14   289.6 2245.82   355.1 2242.22
   369.8 2240.72   422.1 2236.92   461.1 2233.14   486.7 2231.02   532.5 2228.42
   542.7 2228.16   599.8 2228.24   628.4 2227.56   640.6 2227.83   644.7 2227.57
  654.252225.731   656.9  2225.5   665.1 2225.16   669.2 2225.51   681.4 2226.82
   693.7 2229.74   697.7 2231.15     710 2237.59   714.1  2240.8   718.1 2244.66
   722.2 2247.45   726.3 2248.95  751.872251.124   767.1 2251.61   786.8 2250.98
#Mann= 5 ,-1 , 0
       0     .05       0  654.25      .1       0   656.9    .045       0
   669.2      .1       0  751.87     .05       0
#XS Ineff= 2 , 0
          627.06 2230.79
Permanent Ineff=
       F       F
Bank Sta=656.9,669.2
XS Rating Curve= 0 ,0
Exp/Cntr(USF)=0,0
Exp/Cntr=0.5,0.3

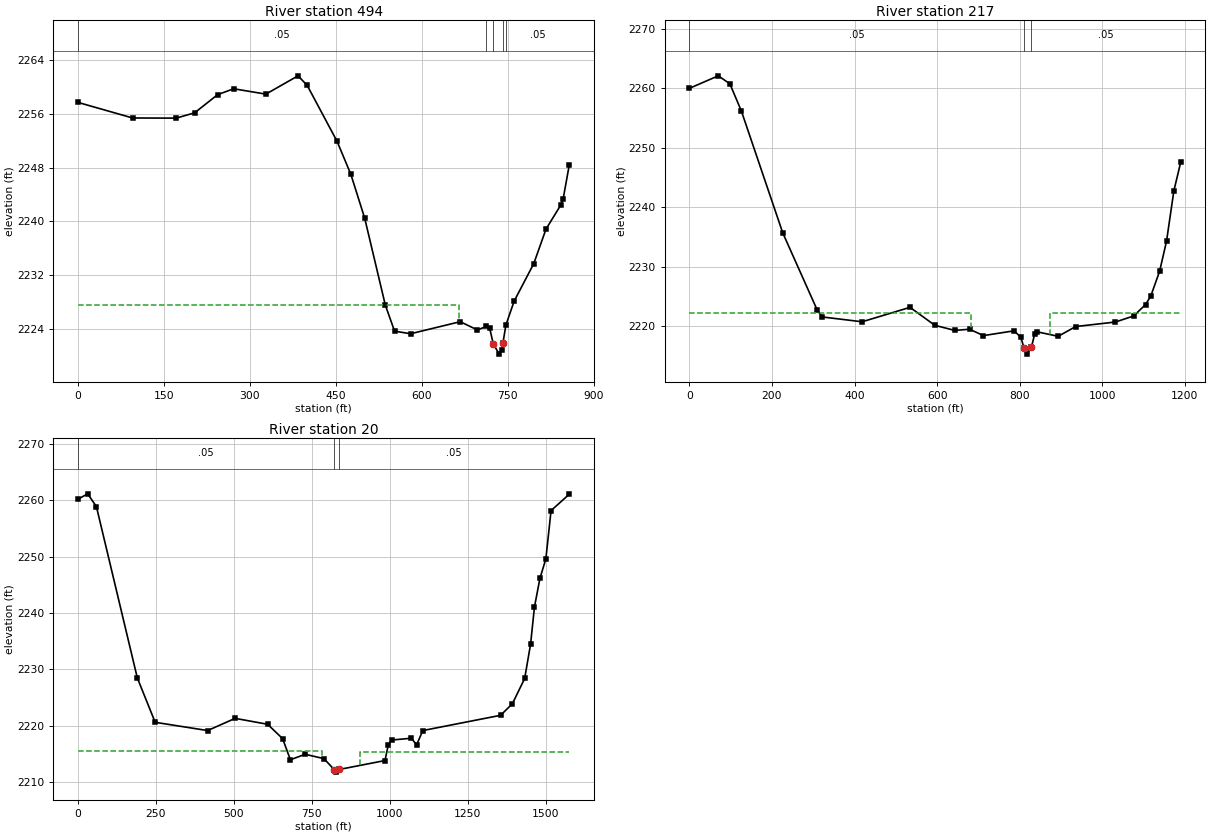
Type RM Length L Ch R = 1 ,494     ,273.7,276.5,280.3
XS GIS Cut Line= 3
 2431048.7688879556793.9213097582431004.56257977556150.719526517
 2430805.6341932556075.568802702
#Sta/Elev= 30
       0 2257.75    95.5 2255.42   171.6  2255.4   203.7 2256.19   243.8  2258.9
   271.8 2259.78     328 2258.98   384.1 2261.71   400.1 2260.28   452.3 2251.92
   476.3    2247   500.4 2240.47   536.4  2227.5   552.5 2223.62   580.5 2223.23
     667 2225.03     697  2223.8  712.742224.322   718.4 2224.07   724.82221.688
   735.2 2220.19   739.8 2220.81   741.72221.911  746.742224.528   761.2 2228.11
   795.4  2233.7   816.7 2238.84   842.4 2242.42   846.7 2243.38   857.4 2248.46
#Mann= 5 ,-1 , 0
       0     .05       0  712.74      .1       0   724.8    .045       0
   741.7      .1       0  746.74     .05       0
#XS Ineff= 2 , 0
          665.55 2227.46
Permanent Ineff=
       F       F
Bank Sta=724.8,741.7
XS Rating Curve= 0 ,0
Exp/Cntr(USF)=0,0
Exp/Cntr=0.3,0.1

Type RM Length L Ch R = 1 ,217     ,194,196.8,197.2
XS GIS Cut Line= 4
2431115.07835009556632.5682850962431081.92361899555920.846724259
 2430944.8840638555825.8031617872430650.91211476555927.477670478
#Sta/Elev= 30
       0 2259.96    69.9 2262.06      98 2260.73     126 2256.14   226.1 2235.71
   309.1 2222.83   321.7 2221.59   418.3 2220.78   534.4  2223.2   594.4 2220.19
   642.5 2219.33   678.6 2219.53   712.2 2218.46   786.3 2219.26   802.9 2218.19
   810.5 2216.35   817.5 2215.35   828.4 2216.51   836.3 2218.72   841.9  2219.1
   893.3 2218.34   935.6 2219.98    1032 2220.74    1076 2221.76  1104.9 2223.67
  1117.6 2225.12  1138.9 2229.26  1155.7 2234.33  1173.5  2242.8  1190.3 2247.65
#Mann= 3 ,-1 , 0
       0     .05       0   810.5    .045       0   828.4     .05       0
#XS Ineff= 2 , 0
           680.9 2222.32  874.58         2222.32
Permanent Ineff=
       F       F
Bank Sta=810.5,828.4
XS Rating Curve= 0 ,0
Exp/Cntr(USF)=0,0
Exp/Cntr=0.3,0.1

Type RM Length L Ch R = 1 ,20      ,,,
XS GIS Cut Line= 4
2431153.61768713556638.2047675452431196.23468173555842.687534996
2431082.16056657555709.3039508042430511.23169042555902.759189832
#Sta/Elev= 30
       0 2260.14    31.4  2261.1    59.4 2258.85   190.5 2228.51   247.7 2220.65
   415.9 2219.19     504 2221.35   608.2  2220.3   656.3 2217.75     681 2214.02
   728.4 2214.99   788.4 2214.22  821.35 2212.29     828 2211.83   837.3  2212.3
   984.2 2213.88     995 2216.72  1005.3 2217.51  1068.7 2217.83  1085.6 2216.66
  1105.4 2219.19  1354.7 2221.89  1392.5 2223.94  1431.9 2228.41  1450.8 2234.49
  1463.2 2241.06  1480.8 2246.14  1499.8 2249.59  1516.4 2258.131574.983 2261.04
#Mann= 3 , 0 , 0
       0     .05       0  821.35    .045       0   837.3     .05       0
#XS Ineff= 2 , 0
          781.98 2215.56  905.37         2215.36
Permanent Ineff=
       F       F
Bank Sta=821.35,837.3
XS Rating Curve= 0 ,0
Exp/Cntr(USF)=0,0
Exp/Cntr=0.3,0.1
LCMann Table=0

Chan Stop Cuts=-1
Use User Specified Reach Order=0
Composite Channel Slope=5